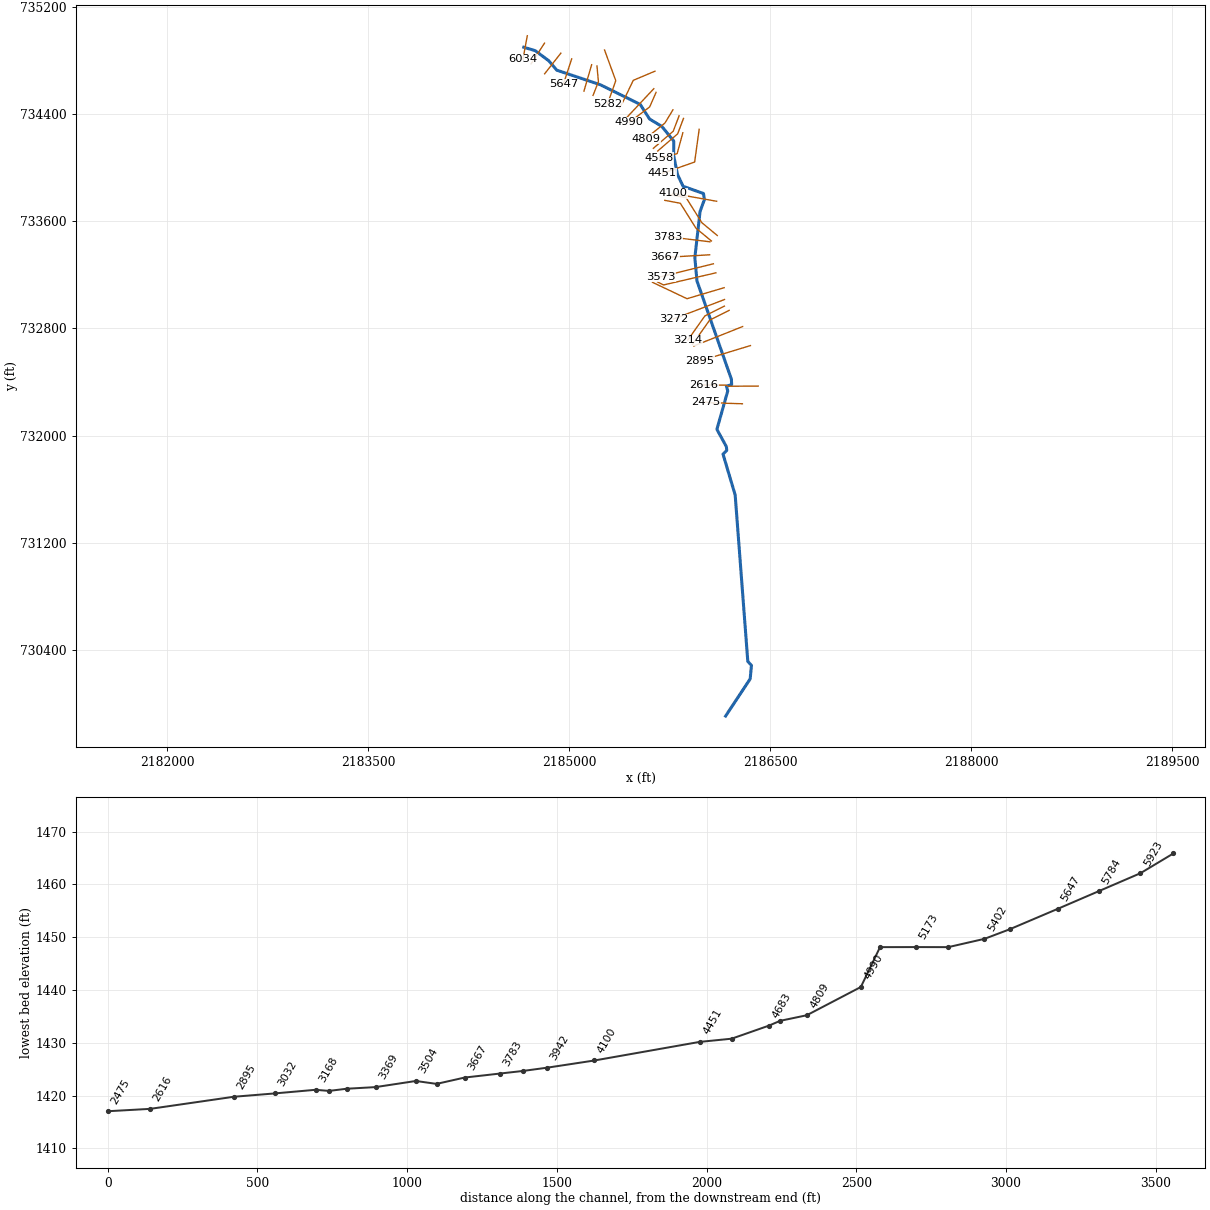
--- FINKRNT1.prj (project) ---

Proj Title=FINKRNT1
Current Plan=p01
Default Exp/Contr=0,0
English Units
Geom File=g01
Flow File=f01
Plan File=p01
BEGIN DESCRIPTION:
---------- MODELED AS PART OF WVEMD CTP PROGRAM, 2023----------
Stream Name: Fink Run Tributary 1
Flood Zone:  AFH
Upshur County, WV
HEC-RAS Version: RAS 6.3
Vertical Datum: NAVD88
Projection: NAD 1983 StatePlane West Virginia S FIPS 4702 (US Feet)
Terrain: 1-meter LIDAR (FEMA Region III 3DEP collected 2016-2018)
Land Use: 2019 NLCD
Hydrologic Method:
WV SIR2010-5033 regression equations
Additional Model Notes:
Signifcant piped flow downstream of station 1732
END DESCRIPTION:
DSS Export Rating Curves= 0
DSS Export Rating Curve Sorted= 0
DSS Export Volume Flow Curves= 0
DXF OffsetX= 0
DXF OffsetY= 0
DXF ScaleX= 0
DXF ScaleY= 0

--- FINKRNT1.p01 (plan) ---

Plan Title=Floodplain
Program Version=4.10
Short Identifier=Floodplain
Geom File=g01
Flow File=f01
Subcritical Flow
K Sum by GR= 0
Std Step Tol= 0.01
Critical Tol= 0.01
Num of Std Step Trials= 20
Max Error Tol= 0.3
Flow Tol Ratio= 0.001
Split Flow NTrial= 30
Split Flow Tol= 0.02
Split Flow Ratio= 0.02
Log Output Level= 0
Friction Slope Method= 1
Unsteady Friction Slope Method= 2
Unsteady Bridges Friction Slope Method= 1
Parabolic Critical Depth
Global Vel Dist= 0 , 0 , 0
Global Log Level= 0
CheckData=True
Encroach Param=-1 ,0,0, 0
Run HTab= 0
Run UNet= 0
Run PostProcess= 0
Run WQNet= 0
UNET Theta= 0
UNET Theta Warmup= 0
UNET ZTol= 0
UNET ZSATol= 0
UNET MxIter= 0
UNET MaxInSteps= 0
UNET DtIC= 0
UNET DtMin= 0
UNET MaxCRTS= 0
UNET WFStab= 0
UNET SFStab= 0
UNET WFX= 1
UNET SFX= 1
UNET DSS MLevel= 1
UNET DZMax Abort= 0
UNET Convert EG Bridges= 0
UNET Use Existing IB Tables= 0
UNET Froude Reduction=False
UNET Froude Limit= 0
UNET Froude Power= 0
UNET Time Slicing=0,0, 5
UNET Junction Losses=0
Write IC File= 0
Write IC File at Sim End=0
Echo Input=False
Echo Parameters=False
Echo Output=False
Write Detailed= 0
WQ AD Non Conservative
WQ ULTIMATE=-1
WQ Max Comp Step=1HOUR
WQ Output Interval=15MIN
WQ Output Selected Increments= 0
WQ Output face flow=0
WQ Output face velocity=0
WQ Output face area=0
WQ Output face dispersion=0
WQ Output cell volume=0
WQ Output cell surface area=0
WQ Output cell continuity=0
WQ Output cumulative cell continuity=0
WQ Output face conc=0
WQ Output face dconc_dx=0
WQ Output face courant=0
WQ Output face peclet=0
WQ Output face adv mass=0
WQ Output face disp mass=0
WQ Output cell mass=0
WQ Output cell source sink temp=0
WQ Output cell source sink nsm=0
WQ Output MaxMinRange=-1
WQ Daily Max Min Mean=-1
WQ Daily Range=0
WQ Daily Time=0
WQ Create Restart=0
WQ Fixed Restart=0
WQ System Summary=0
WQ Use Fixed Temperature=0
Sorting and Armoring Iterations= 10
XS Update Threshold= 0.02
Hydraulics Update Threshold= 0.02
Energy Slope Method= 1
Volume Change Method= 1
XS Weighting Method= 0
Number of US Weighted Cross Sections= 1
Number of DS Weighted Cross Sections= 1
Upstream XS Weight=0
Main XS Weight=1
Downstream XS Weight=0
Number of DS XS's Weighted with US Boundary= 1
Upstream Boundary Weight= 1
Weight of XSs Associated with US Boundary= 0
Number of US XS's Weighted with DS Boundary= 1
Downstream Boundary Weight= 0.5
Weight of XSs Associated with DS Boundary= 0.5
Sediment Output Level= 3
Mass or Volume Output= 0
Output Increment Type= 1
Profile and TS Output Increment= 1
XS Output Flag= 0
XS Output Increment= 10
Disregard all LS=0
Disregard all Conn=0
Disregard all Breaches=0
Disregard all Pumps=0

--- FINKRNT1.f01 (steady flow) ---

Flow Title=Flows
Program Version=4.10
Number of Profiles= 1
Profile Names=01pct
River Rch & RM=FINKRNT1,Main            ,6034
     136
River Rch & RM=FINKRNT1,Main            ,3272
     189
River Rch & RM=FINKRNT1,Main            ,3032
     217
River Rch & RM=FINKRNT1,Main            ,1789
     249
Boundary for River Rch & Prof#=FINKRNT1,Main            , 1
Up Type= 0
Dn Type= 3
Dn Slope=0.00542
DSS Import GetInterval= 0
DSS Import GetPeak= 0
DSS Import FillOption= 0

--- FINKRNT1.g01 (geometry) ---

Geom Title=Geometry
Program Version=6.30

River Reach=FINKRNT1        ,Main
Reach XY= 30
 2184661.0913889734897.3231528622184746.29691626734871.745901435
2184847.29439368734796.4499557972184907.16123349734726.335471536
 2185231.0749868 734617.97406669  2185529.512382734471.099032342
2185599.74154739734361.4107929842185690.68377717734307.030243388
2185779.96685108734197.3626821432185779.51414096734089.112070125
2185808.30441023733946.7305193792185849.82473353733859.640609592
2186001.92002948733805.858042372 2186008.6790746733760.161477834
2185976.39320189 733671.840838172185937.49844266733327.522579357
2185953.34711139733153.5554304632186209.87995492732421.008768186
2186212.31163704732380.1744582722186172.59201688732367.612668499
2186183.20405915732332.9279641132186101.97713082732046.072228998
2186172.60163519731917.1156626052186175.57704644731888.887962818
2186147.72005878731861.0285415952186238.34400004731556.373999998
2186332.65284498730314.1462538542186359.82687742730284.438829616
2186350.34743984730183.5837640022186166.92309801729906.354460612

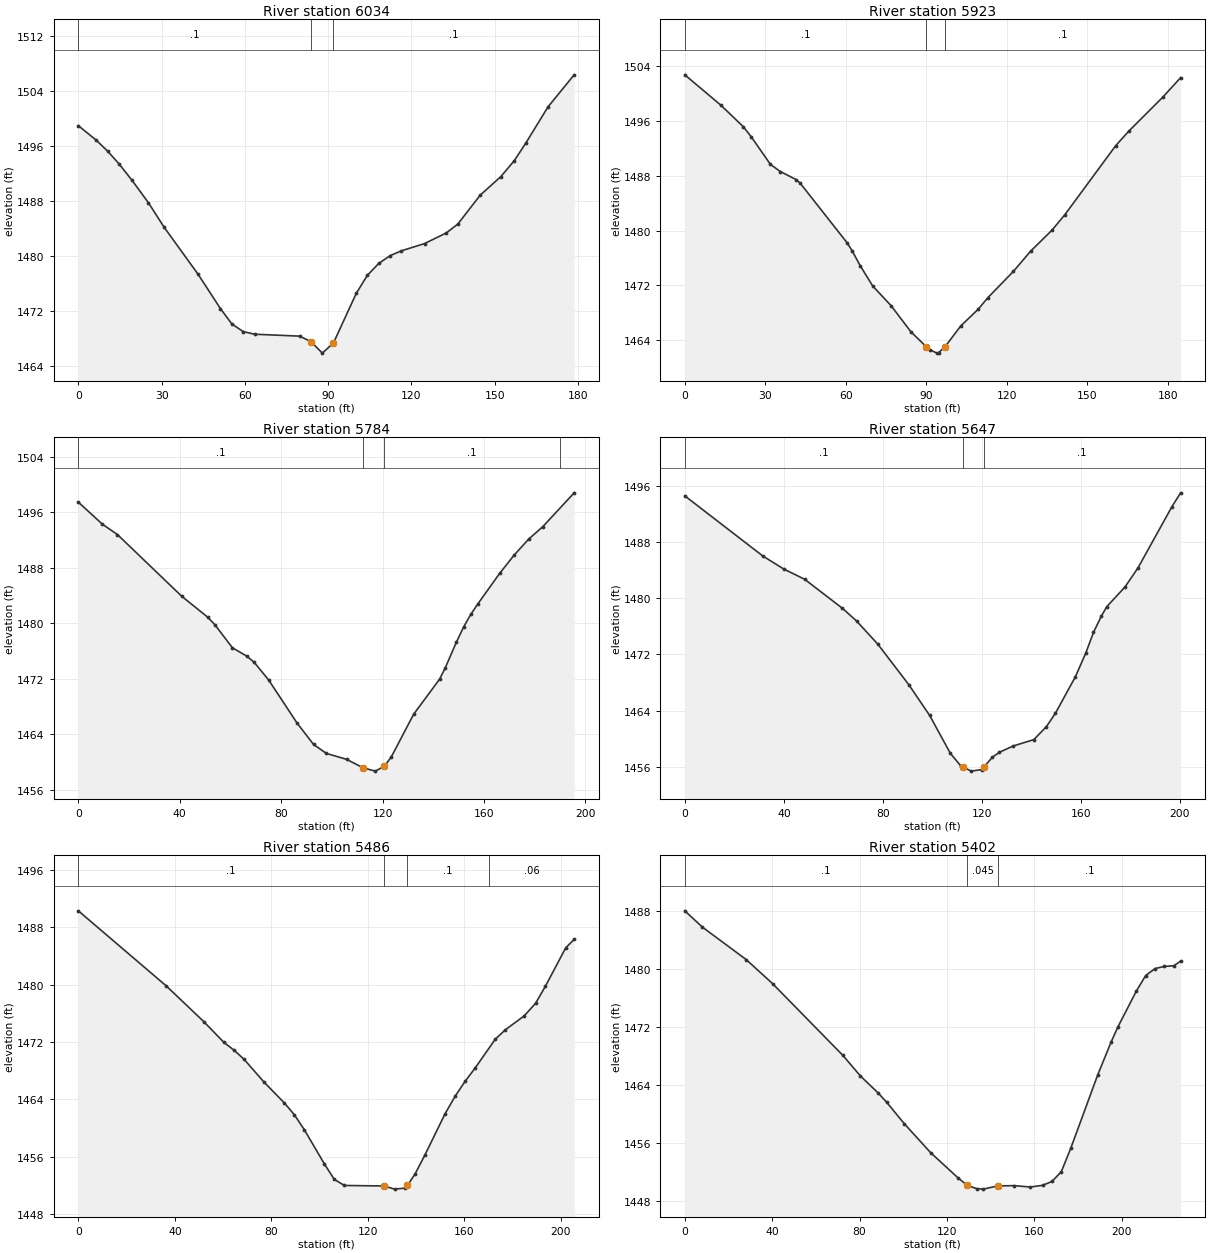
Type RM Length L Ch R = 1 ,6034    ,111.6,110.6,108.7
XS GIS Cut Line= 2
2184687.13590922734983.5675707392184654.56896472734807.961497467
#Sta/Elev= 30
       0 1498.96     6.5 1496.83    10.6 1495.23    14.6 1493.43    19.3 1491.03
    25.2 1487.78    30.9 1484.19    43.1 1477.37    51.2 1472.35    55.3 1470.12
    59.4 1469.01    63.5 1468.63    79.7 1468.35    83.8 1467.55    87.9 1465.88
    91.9 1467.36   100.1 1474.56   104.1 1477.19   108.2 1478.92   112.3 1480.05
   116.3 1480.75   124.7 1481.81   132.6 1483.37   136.7 1484.65   144.8 1488.87
   152.2 1491.55     157 1493.85   161.1 1496.37   169.2  1501.7   178.6 1506.35
#Mann= 3 ,-1,0
       0      .1       0    83.8    .045       0    91.9      .1       0
Bank Sta=83.8,91.9
XS Rating Curve= 0 ,0
Exp/Cntr(USF)=0,0
Exp/Cntr=0.3,0.1

Type RM Length L Ch R = 1 ,5923    ,139.2,139.2,138.7
XS GIS Cut Line= 2
2184815.48798459734928.0121948312184715.23288094734772.840282812
#Sta/Elev= 30
       0 1502.71    13.5 1498.26    21.8 1495.14    24.7  1493.7    31.9 1489.65
    35.6  1488.6    41.5 1487.43      43  1486.9    60.5 1478.19    62.3 1477.07
    65.3  1474.9      70 1471.91    76.8 1469.06    84.3  1465.2   89.891463.077
    91.2 1462.64    93.9 1462.12    94.6 1462.21      97 1463.08   102.8 1466.09
   109.3 1468.52   112.9 1470.21   122.4 1474.04   128.8 1476.98   136.7 1480.02
   141.5 1482.27   160.5 1492.37   165.3 1494.46     178 1499.43   184.7  1502.3
#Mann= 3 ,-1,0
       0      .1       0   89.89    .045       0      97      .1       0
Bank Sta=89.89,97
XS Rating Curve= 0 ,0
Exp/Cntr(USF)=0,0
Exp/Cntr=0.3,0.1

Type RM Length L Ch R = 1 ,5784    ,134.8,136.7,137.6
XS GIS Cut Line= 2
2184937.45438457734853.2997927482184816.76511967734699.405015807
#Sta/Elev= 30
       0 1497.44     9.5 1494.26    15.4 1492.78    40.8 1483.89      51 1480.89
    53.9 1479.78    60.8 1476.47    66.5 1475.26    69.4 1474.37    75.1 1471.83
    86.3 1465.63    92.8 1462.56    97.9 1461.26   105.8 1460.42   112.3 1459.21
   117.1 1458.72   120.7  1459.4   123.5 1460.79   132.3 1466.92   142.5 1471.95
   144.7 1473.54   149.1 1477.25     152 1479.47   154.8 1481.27   157.7 1482.84
   166.2 1487.18   171.9  1489.8   177.6  1492.1   183.2  1493.9   195.6 1498.78
#Mann= 4 ,-1,0
       0      .1       0   112.3    .045       0   120.7      .1       0
     190     .06       0
Bank Sta=112.3,120.7
XS Rating Curve= 0 ,0
Exp/Cntr(USF)=0,0
Exp/Cntr=0.3,0.1

Type RM Length L Ch R = 1 ,5647    ,160.7,160.9,161.3
XS GIS Cut Line= 2
2185018.55246205734811.1543351622184956.15802779734620.861208489
#Sta/Elev= 30
       0 1494.53    31.5 1485.98      40 1484.12    48.4 1482.67    63.7 1478.53
    69.4 1476.73    77.9 1473.47    90.5 1467.67    98.9 1463.31   107.3  1457.9
   111.5 1456.12 112.3731455.976   115.7 1455.38   119.9  1455.6   120.7  1455.9
   124.2 1457.34   127.1 1458.06   132.6 1458.95     141 1459.86   146.1 1461.72
   149.7  1463.6   157.8 1468.81     162 1472.18   165.1 1475.11   168.3 1477.44
   170.5 1478.78   177.8 1481.56   183.1  1484.3   196.8    1493   200.3 1494.96
#Mann= 3 ,-1,0
       0      .1       0 112.373    .045       0   120.7      .1       0
Bank Sta=112.373,120.7
XS Rating Curve= 0 ,0
Exp/Cntr(USF)=0,0
Exp/Cntr=0.3,0.1

Type RM Length L Ch R = 1 ,5486    ,84.3,83.8,82.5
XS GIS Cut Line= 2
2185167.33869867 734767.093174962185109.86762015734569.775805355
#Sta/Elev= 30
       0 1490.28    36.4 1479.83      52 1474.84    60.3 1471.96    64.5 1470.87
    68.7 1469.59      77  1466.4    85.3 1463.54    89.5 1461.88    93.7 1459.76
     102    1455   106.1 1452.85   110.3 1452.01   126.7 1451.94   131.1  1451.5
   135.3 1451.64   136.4 1452.01   139.5 1453.57   143.6 1456.23     152    1462
   156.1 1464.41   160.3 1466.52   164.5 1468.39   172.8 1472.39     177 1473.71
   184.8 1475.64   189.5 1477.39   193.6 1479.78     202 1485.12   205.5  1486.3
#Mann= 4 ,-1,0
       0      .1       0   126.7    .045       0   136.4      .1       0
     170     .06       0
Bank Sta=126.7,136.4
XS Rating Curve= 0 ,0
Exp/Cntr(USF)=0,0
Exp/Cntr=0.3,0.1

Type RM Length L Ch R = 1 ,5402    ,128.2,120.9,121.7
XS GIS Cut Line= 3
2185207.13884526734757.2086714242185217.77307736734640.232118268
2185177.89470697734538.320727261
#Sta/Elev= 30
       0    1488     8.1 1485.75    28.1 1481.29    40.2 1477.97    72.3 1468.12
    80.4 1465.26    88.4 1462.96    92.4 1461.65   100.4 1458.72   112.5 1454.72
     125 1451.26   129.3  1450.2   133.6 1449.77   136.5  1449.7   143.31450.143
   150.8 1450.18   158.1 1449.99   163.7 1450.22     168 1450.75   172.3  1452.1
   176.6  1455.3     189 1465.45   195.1 1469.95   198.2 1472.03   206.6 1476.93
   210.9 1479.09   215.2 1480.06   219.5 1480.35   223.8 1480.44   226.9 1481.08
#Mann= 3 ,-1,0
       0      .1       0   129.3    .045       0   143.3      .1       0
Bank Sta=129.3,143.3
XS Rating Curve= 0 ,0
Exp/Cntr(USF)=0,0
Exp/Cntr=0.3,0.1

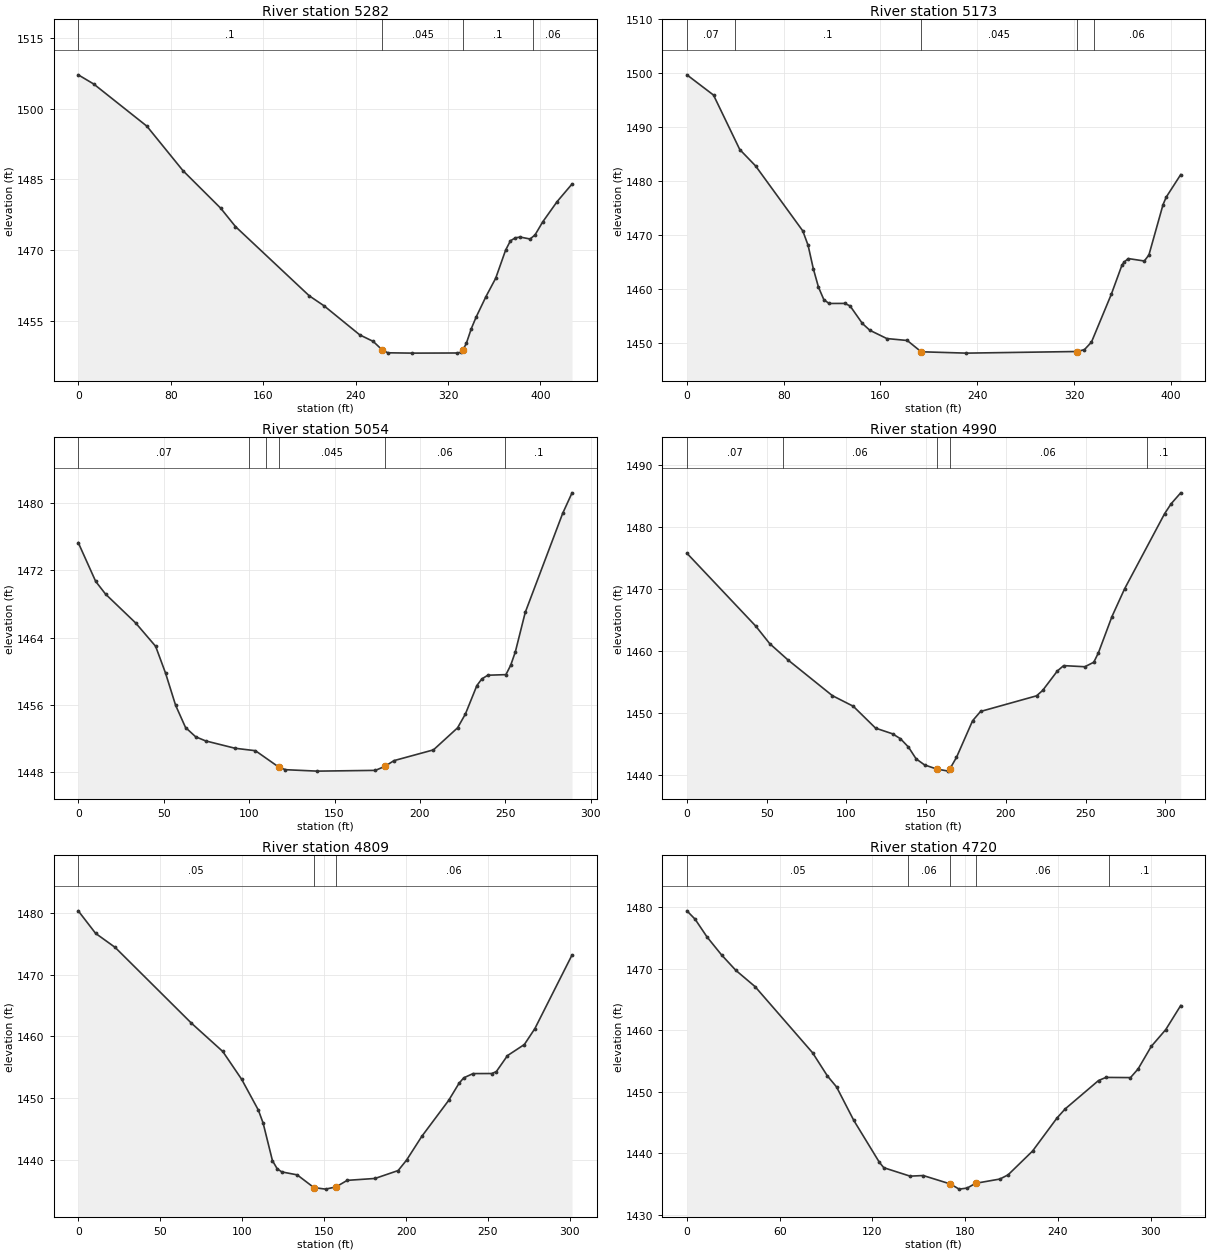
Type RM Length L Ch R = 1 ,5282    ,129.9,109.1,107.3
XS GIS Cut Line= 3
2185263.58709084734876.9827499942185347.32709159734648.093414589
 2185285.9177577734475.030746356
#Sta/Elev= 30
       0 1507.22    13.4 1505.27    59.4 1496.32    90.7 1486.86   123.3  1478.9
   136.1    1475     200 1460.29   212.8 1458.17   243.7    1452   255.3 1450.62
   263.1 1448.81     268  1448.2   289.3 1448.13   327.5 1448.16   331.7 1448.32
   333.1 1448.84     336 1450.27   340.2 1453.33   344.4 1455.79   352.9 1460.14
   361.3 1464.02   369.9    1470   374.1 1471.99   378.4 1472.62   382.6 1472.77
   391.1 1472.36   395.4 1473.24     402 1475.99   414.5 1480.31   427.4 1484.04
#Mann= 4 ,-1,0
       0      .1       0   263.1    .045       0   333.1      .1       0
  393.73     .06       0
Bank Sta=263.1,333.1
XS Rating Curve= 0 ,0
Exp/Cntr(USF)=0,0
Exp/Cntr=0.3,0.1

Type RM Length L Ch R = 1 ,5173    ,156.3,118.7,112.2
XS GIS Cut Line= 4
2185640.49171287734718.9459389912185478.08608592734650.564622378
2185396.88327244734481.7482469872185374.08950023734443.283756392
#Sta/Elev= 30
       0  1499.7      22 1495.95    43.7 1485.86    56.8 1482.82    95.8 1470.79
   100.2 1468.11   104.5 1463.79   108.8 1460.35   113.2 1458.06   117.5 1457.34
   130.5 1457.35   134.9 1456.89   145.1 1453.63   151.2 1452.38   165.3 1450.84
   182.2 1450.48   193.7 1448.39     231 1448.14   322.5 1448.44   328.7 1448.79
   334.5 1450.18   350.9 1459.04   359.7 1464.44   361.5 1465.01   364.9 1465.66
   378.2 1465.21     382 1466.33   393.7 1475.67   396.3 1477.04   408.3 1481.22
#Mann= 5 ,-1,0
       0     .07       0      40      .1       0   193.7    .045       0
   322.5      .1       0  336.21     .06       0
Bank Sta=193.7,322.5
XS Rating Curve= 0 ,0
Exp/Cntr(USF)=0,0
Exp/Cntr=0.3,0.1

Type RM Length L Ch R = 1 ,5054    ,77.2,64.1,64.4
XS GIS Cut Line= 2
2185631.13284719734588.0197266162185433.42939777 734377.15710827
#Sta/Elev= 30
       0 1475.32    10.2 1470.71      16 1469.19    33.6 1465.76    45.3 1462.98
    51.1 1459.79      57 1455.96    62.8 1453.32    68.7 1452.22    74.5 1451.73
    91.8 1450.85   103.7 1450.56   117.3 1448.62   121.3  1448.3   139.9 1448.13
   173.9 1448.22   179.4 1448.69   184.8 1449.38   207.9 1450.66     222 1453.28
   226.6 1454.93   233.3 1458.31   236.2  1459.1   239.7 1459.54   250.3 1459.61
   253.1 1460.73   255.8 1462.31   261.6 1467.01   283.5 1478.79     289 1481.24
#Mann= 6 ,-1,0
       0     .07       0     100      .1       0     110     .06       0
   117.3    .045       0   179.4     .06       0     250      .1       0
Bank Sta=117.3,179.4
XS Rating Curve= 0 ,0
Exp/Cntr(USF)=0,0
Exp/Cntr=0.3,0.1

Type RM Length L Ch R = 1 ,4990    ,180.5,180.6,179.6
XS GIS Cut Line= 3
2185647.99929004734560.7753593182185600.60543315734452.360684411
 2185448.0805483734336.866444305
#Sta/Elev= 30
       0 1475.71    43.2 1463.95    51.9 1461.14    63.3 1458.52    91.2 1452.75
   104.3 1451.04   118.3 1447.51   128.9  1446.6   133.9  1445.8   138.9 1444.46
   143.7 1442.56     149 1441.58   156.7 1440.91     164 1440.58  164.691440.867
     169 1442.79   179.1  1448.7   184.1  1450.2   219.2 1452.72     223 1453.58
   232.3 1456.74   236.2 1457.59   249.5 1457.41   255.1 1458.14     258 1459.66
   266.5 1465.51   274.4 1469.97   299.5 1482.09   303.6 1483.69   309.6 1485.45
#Mann= 5 ,-1,0
       0     .07       0      60     .06       0   156.7    .045       0
  164.69     .06       0  288.32      .1       0
Bank Sta=156.7,164.69
XS Rating Curve= 0 ,0
Exp/Cntr(USF)=0,0
Exp/Cntr=0.3,0.1

Type RM Length L Ch R = 1 ,4809    ,88.6,89.1,89.5
XS GIS Cut Line= 3
2185774.06864766734430.2675289512185713.32074703734330.641829746
2185569.49192231734214.929918128
#Sta/Elev= 30
       0 1480.32    10.6 1476.67    22.5  1474.4    69.1 1462.11    88.2 1457.53
    99.7 1453.03   109.9 1448.04   112.8 1445.94   118.5 1439.84   121.4 1438.53
   124.2 1438.02   133.6 1437.54   143.8 1435.48   150.9 1435.23   157.3 1435.59
   164.1 1436.65   181.1 1436.96   195.2 1438.24   200.3 1439.92   209.6 1443.77
     226  1449.6   232.3 1452.36   235.2 1453.26   240.9 1453.95   252.3 1453.96
   255.1 1454.27   261.9 1456.86   272.2 1458.66   278.6 1461.23   301.3 1473.17
#Mann= 3 ,-1,0
       0     .05       0   143.8    .045       0   157.3     .06       0
Bank Sta=143.8,157.3
XS Rating Curve= 0 ,0
Exp/Cntr(USF)=0,0
Exp/Cntr=0.3,0.1

Type RM Length L Ch R = 1 ,4720    ,36.8,37,36.7
XS GIS Cut Line= 3
2185820.03164476734386.1489707132185776.27913681734271.038028756
2185627.53893197734142.829530394
#Sta/Elev= 30
       0 1479.41     5.3 1478.05      13 1475.17    22.4 1472.25    31.6 1469.75
    44.1 1467.09    81.3 1456.34    90.9 1452.57    96.8 1450.79     108 1445.33
   124.5 1438.54   127.4 1437.65   144.4 1436.28   152.9 1436.38   170.51435.005
   176.1 1434.17   181.3 1434.34   186.81435.115   202.5 1435.81   207.8 1436.49
   223.6 1440.35   239.5 1445.75   244.7  1447.2   266.3 1451.82   271.1 1452.33
     287  1452.3   291.9  1453.7   300.4 1457.36   309.8  1460.1   319.5 1464.02
#Mann= 5 ,-1,0
       0     .05       0  143.15     .06       0   170.5    .045       0
   186.8     .06       0  273.15      .1       0
Bank Sta=170.5,186.8
XS Rating Curve= 0 ,0
Exp/Cntr(USF)=0,0
Exp/Cntr=0.3,0.1

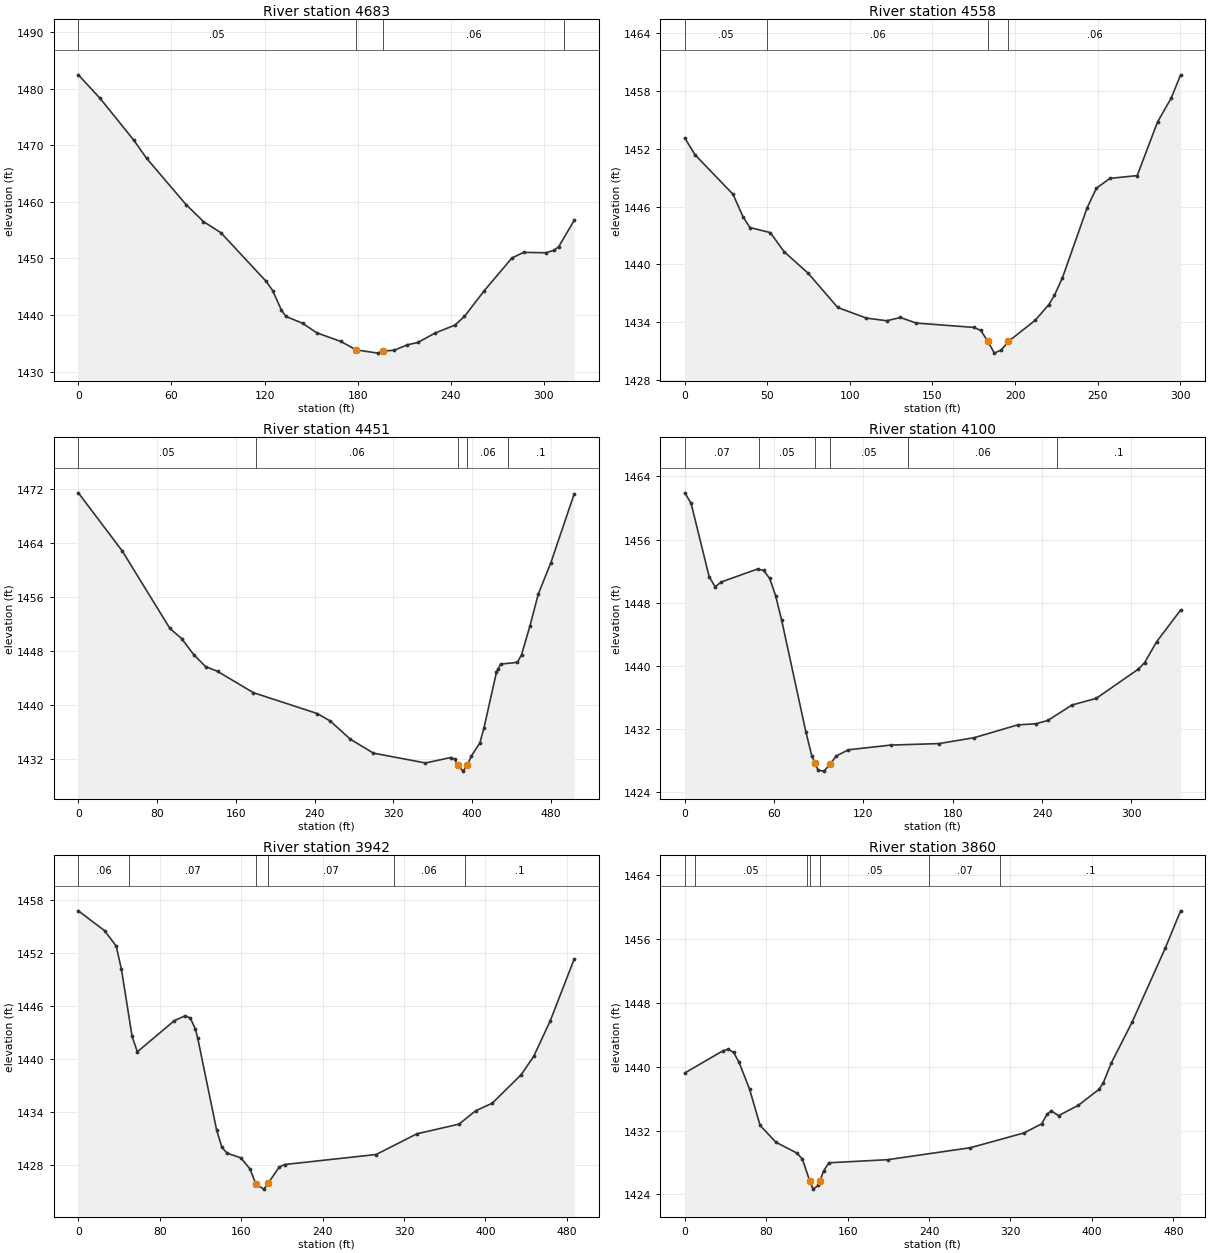
Type RM Length L Ch R = 1 ,4683    ,128.4,124.7,120.9
XS GIS Cut Line= 3
2185852.82389281734366.3286809932185809.07138486734251.217739036
2185660.33118002734123.009240674
#Sta/Elev= 30
       0 1482.42    14.1 1478.24    35.6 1470.93      44 1467.67    69.4 1459.51
    80.6 1456.51    91.9 1454.53     121 1445.95   125.2 1444.33   130.9 1440.85
   133.7 1439.76   144.6 1438.53   153.6 1436.86   169.2 1435.33   178.91433.848
     193 1433.27   196.41433.645   203.5 1433.77     212 1434.74   218.8 1435.15
   229.9 1436.82   242.7 1438.22   248.8 1439.75   261.6 1444.31   279.4 1450.07
   286.9 1451.06   301.1    1451   306.7 1451.44   309.6  1452.1   319.5 1456.71
#Mann= 4 ,-1,0
       0     .05       0   178.9    .045       0   196.4     .06       0
  313.15      .1       0
Bank Sta=178.9,196.4
XS Rating Curve= 0 ,0
Exp/Cntr(USF)=0,0
Exp/Cntr=0.3,0.1

Type RM Length L Ch R = 1 ,4558    ,106.5,107.2,107.3
XS GIS Cut Line= 3
2185847.85132959734259.1721345012185805.31440117 734103.20339696
2185670.61412784734070.414514636
#Sta/Elev= 30
       0 1453.12     6.2 1451.38    29.2 1447.28    35.2 1444.97    39.4 1443.83
    51.8  1443.3    60.1 1441.33    74.8 1439.07    92.6 1435.53   109.9 1434.43
   122.3 1434.15   130.6 1434.49   140.1 1433.91   175.2 1433.46   179.3 1433.14
   183.4 1432.05   187.5 1430.79   191.7 1431.12     1961432.001   212.2  1434.2
   220.5 1435.83   223.9  1436.8   228.7  1438.6   243.7 1445.89   249.3 1447.91
   257.5 1448.93     274 1449.22   286.3 1454.78   294.6 1457.27   300.3 1459.68
#Mann= 4 ,-1,0
       0     .05       0      50     .06       0   183.4    .045       0
     196     .06       0
Bank Sta=183.4,196
XS Rating Curve= 0 ,0
Exp/Cntr(USF)=0,0
Exp/Cntr=0.3,0.1

Type RM Length L Ch R = 1 ,4451    ,352.9,351.3,347.7
XS GIS Cut Line= 3
2185969.61722416734285.2222008862185936.09321239734040.821340833
 2185693.8551918733955.389181787
#Sta/Elev= 30
       0 1471.45    44.5 1462.85    92.9 1451.36     105 1449.83   117.1 1447.47
   129.2 1445.69   141.4 1444.98   177.7 1441.82   242.7 1438.72   255.8 1437.62
   276.3 1434.91   299.7 1432.85   352.6 1431.39   378.1 1432.19   382.3 1431.96
  385.231431.045   390.8 1430.18   395.1 1431.06   399.3 1432.45   407.8 1434.36
     412 1436.59   424.7 1444.87     426 1445.26     429 1446.05     446 1446.31
   450.2 1447.46   458.7 1451.71   467.2 1456.46   479.9 1461.07   503.6 1471.28
#Mann= 5 ,-1,0
       0     .05       0     180     .06       0  385.23    .045       0
   395.1     .06       0  436.69      .1       0
Bank Sta=385.23,395.1
XS Rating Curve= 0 ,0
Exp/Cntr(USF)=0,0
Exp/Cntr=0.3,0.1

Type RM Length L Ch R = 1 ,4100    ,162.2,157.6,153
XS GIS Cut Line= 2
2186100.27560836733747.9699163972185772.31993393733806.308185408
#Sta/Elev= 30
       0 1461.93     4.2 1460.61    16.4 1451.28    20.4 1450.03    24.5 1450.63
    48.9 1452.28    52.9 1452.09      57 1451.09      61  1448.9    65.1 1445.77
    81.4 1431.58    85.4 1428.55    87.4 1427.72    89.5 1426.78    93.5 1426.66
    97.6 1427.53   101.7 1428.57   109.8 1429.36   138.2 1429.96   170.7 1430.15
   194.3 1430.89   223.6 1432.52   235.7 1432.66   243.9 1433.08   260.1 1435.04
   276.4 1435.88   304.8  1439.6   308.9 1440.41     317 1443.06   333.1 1447.08
#Mann= 6 ,-1,0
       0     .07       0      50     .05       0    87.4    .045       0
    97.6     .05       0     150     .06       0     250      .1       0
Bank Sta=87.4,97.6
XS Rating Curve= 0 ,0
Exp/Cntr(USF)=0,0
Exp/Cntr=0.3,0.1

Type RM Length L Ch R = 1 ,3942    ,80,82.2,84.2
XS GIS Cut Line= 4
2186104.84216073733492.7078441862185989.46435029733588.306601412
2185872.43828541733774.5593525582185757.06047497733795.986660212
#Sta/Elev= 30
       0 1456.73    25.8 1454.49    37.2 1452.75    42.4 1450.11    52.8 1442.56
      58 1440.81    94.4 1444.33   104.8 1444.87     110 1444.63   115.1 1443.36
   117.3 1442.36   135.9 1431.96   141.1 1430.02   146.3 1429.35   159.8 1428.83
   168.8 1427.56   174.5 1425.84   182.3  1425.3   186.6 1425.97   197.4  1427.8
   202.8 1428.08   292.6 1429.21   332.7 1431.55   374.1 1432.64   390.4 1434.15
   406.7    1435   435.2 1438.23   447.4 1440.29   463.6 1444.28   487.2 1451.27
#Mann= 6 ,-1,0
       0     .06       0      50     .07       0   174.5    .045       0
   186.6     .07       0  309.84     .06       0   379.8      .1       0
Bank Sta=174.5,186.6
XS Rating Curve= 0 ,0
Exp/Cntr(USF)=0,0
Exp/Cntr=0.3,0.1

Type RM Length L Ch R = 1 ,3860    ,73.9,76.8,79.1
XS GIS Cut Line= 4
2186061.16341821733451.5014833142185945.78560776733547.100240539
2185828.75954288733733.3529916852185713.38173244733754.780299339
#Sta/Elev= 30
       0 1439.22    37.6 1442.01    42.8 1442.18      48 1441.79    53.2 1440.59
    63.6  1437.2      74 1432.65    89.6 1430.54   110.4 1429.17   115.6 1428.41
  122.931425.633     126 1424.67   131.2 1425.14   132.6 1425.63   136.3 1426.92
   141.5 1427.97   199.5 1428.36   280.7 1429.86   333.3 1431.71   350.7 1432.85
   355.9 1434.04   360.1 1434.48   367.2 1433.87   386.7 1435.17     407 1437.17
   411.1 1437.96   419.2  1440.5   439.6 1445.61   472.1 1454.86   487.2 1459.53
#Mann= 7 ,-1,0
       0     .06       0      10     .05       0     120     .07       0
  122.93    .045       0   132.6     .05       0  239.84     .07       0
  309.84      .1       0
Bank Sta=122.93,132.6
XS Rating Curve= 0 ,0
Exp/Cntr(USF)=0,0
Exp/Cntr=0.3,0.1

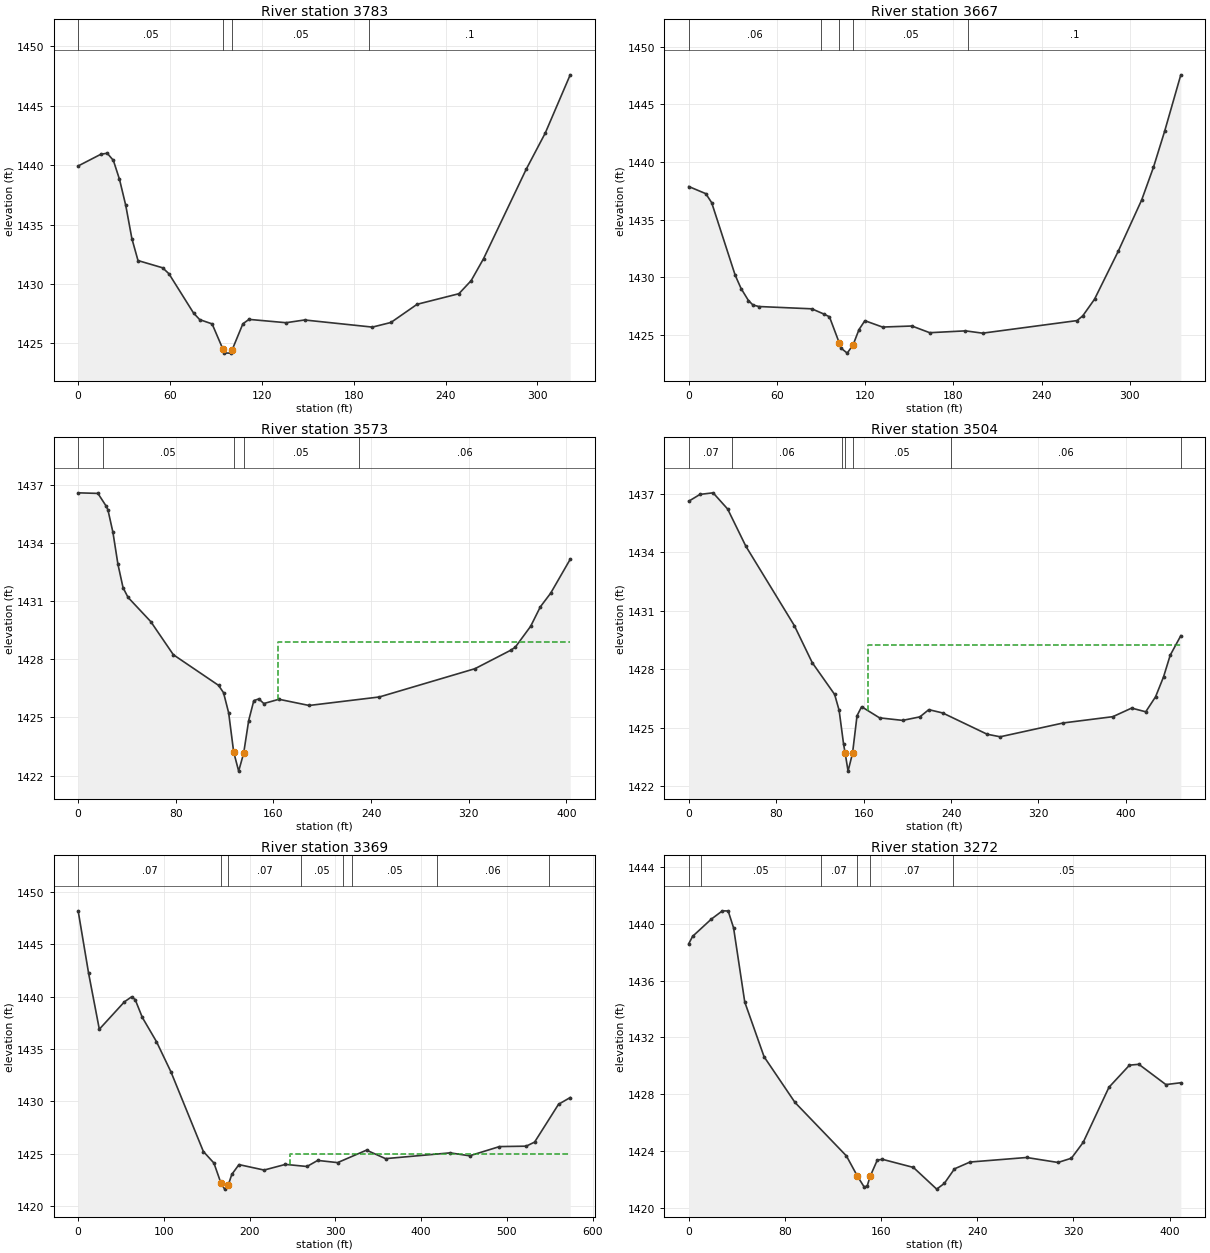
Type RM Length L Ch R = 1 ,3783    ,115.7,116.7,117.3
XS GIS Cut Line= 2
2186051.00179957733445.3616391212185731.98297782733484.292749572
#Sta/Elev= 30
       0 1439.93    14.9 1440.92      19    1441      23  1440.4      27 1438.81
    31.1 1436.61    35.1 1433.82    39.1 1431.97    55.2 1431.36    59.3 1430.86
    75.4 1427.55    79.4    1427    87.5 1426.64    94.51424.532    95.5 1424.19
    99.6 1424.18   100.51424.428   107.6 1426.65   111.6 1427.02   135.8 1426.74
   147.9 1426.97   192.2 1426.37   204.3 1426.76   221.4 1428.29   248.7 1429.18
   256.7 1430.28   264.8 1432.13   292.6 1439.64   305.1  1442.7   321.4  1447.6
#Mann= 4 ,-1,0
       0     .05       0    94.5    .045       0   100.5     .05       0
     190      .1       0
Bank Sta=94.5,100.5
XS Rating Curve= 0 ,0
Exp/Cntr(USF)=0,0
Exp/Cntr=0.3,0.1

Type RM Length L Ch R = 1 ,3667    ,92.8,93.7,94.3
XS GIS Cut Line= 2
2186047.75754037733348.4664308872185713.59884233733329.000875661
#Sta/Elev= 30
       0 1437.87    11.6 1437.25    15.6 1436.47    31.6 1430.18    35.6 1429.03
    40.6 1427.99    43.7  1427.6    47.7 1427.47    83.7 1427.27    91.7 1426.83
    95.7 1426.58   102.4 1424.31   103.8 1423.84   107.8 1423.43   111.8 1424.15
   115.8 1425.47   119.8 1426.24   131.8 1425.69   151.8 1425.78   163.9  1425.2
   188.2 1425.36   199.9 1425.16   264.1 1426.25     268 1426.66     276  1428.1
   292.1 1432.25   308.1 1436.71   316.1 1439.54   323.7 1442.66   334.7 1447.55
#Mann= 5 ,-1,0
       0     .06       0      90     .05       0   102.4    .045       0
   111.8     .05       0     190      .1       0
Bank Sta=102.4,111.8
XS Rating Curve= 0 ,0
Exp/Cntr(USF)=0,0
Exp/Cntr=0.3,0.1

Type RM Length L Ch R = 1 ,3573    ,69.5,69.2,69.1
XS GIS Cut Line= 2
2186075.87445347733281.4184073322185684.40050949 733185.17205094
#Sta/Elev= 30
       0  1436.6    16.2 1436.57    23.1  1435.9    24.4 1435.72    28.5 1434.56
    32.6 1432.91    36.8  1431.7    40.9  1431.2    59.5 1429.95      78 1428.24
     115 1426.66   119.1 1426.28   123.3 1425.24   127.4 1423.22   131.5 1422.23
   135.6 1423.16   139.7 1424.84   143.9 1425.87     148 1425.96   152.1 1425.72
   164.5 1425.94   189.2 1425.62   246.8 1426.06   325.1 1427.52   354.3 1428.47
   358.1 1428.63   370.7 1429.71   378.6 1430.71   387.1 1431.42   403.1 1433.17
#Mann= 5 ,-1,0
       0     .06       0      20     .05       0   127.4    .045       0
   135.6     .05       0     230     .06       0
#XS Ineff= 2 , 0
                          163.38         1428.89
Permanent Ineff=
       F       F
Bank Sta=127.4,135.6
XS Rating Curve= 0 ,0
Exp/Cntr(USF)=0,0
Exp/Cntr=0.3,0.1

Type RM Length L Ch R = 1 ,3504    ,134.5,134.6,134.8
XS GIS Cut Line= 3
2186094.25858896 733213.829673912185703.86606472733123.531126059
2185659.52785559733145.700230621
#Sta/Elev= 30
       0 1436.61    10.3 1436.96    22.3 1437.04    35.6 1436.21    52.3  1434.3
    96.6 1430.24     113 1428.34   133.5 1426.71   137.6  1425.9   141.7 1424.16
  143.161423.696   145.8 1422.78   149.9  1423.7     154 1425.62   158.2 1426.08
   174.6 1425.51   195.7 1425.38   211.5 1425.56   219.7 1425.93   232.4 1425.76
   273.1 1424.67     285 1424.54   342.9 1425.25   388.1 1425.57   405.3 1426.01
   418.2 1425.82   427.2 1426.59   434.5 1427.61   440.6 1428.72   450.3 1429.72
#Mann= 7 ,-1,0
       0     .07       0      40     .06       0     140     .05       0
  143.16    .045       0   149.9     .05       0     240     .06       0
  450.27     .05       0
#XS Ineff= 2 , 0
                          163.94         1429.26
Permanent Ineff=
       F       F
Bank Sta=143.16,149.9
XS Rating Curve= 0 ,0
Exp/Cntr(USF)=0,0
Exp/Cntr=0.3,0.1

Type RM Length L Ch R = 1 ,3369    ,96.2,96.6,96.9
XS GIS Cut Line= 3
2186155.89951384733102.9841510982185879.05606175733020.796251257
2185621.67816487733142.996681284
#Sta/Elev= 30
       0 1448.18    12.2 1442.22    24.7 1436.88      54  1439.5    62.3 1439.97
    66.5 1439.71    74.8 1438.01    91.3  1435.7   108.2 1432.81     146 1425.21
   158.3 1424.11   166.6 1422.17   170.8 1421.62     175    1422   179.1 1423.02
   187.5 1423.96   216.8 1423.44   241.7 1423.98   266.8 1423.78   279.3 1424.36
   302.5 1424.15   336.2 1425.34   358.4 1424.53   433.7 1425.08   456.4  1424.8
   491.2 1425.68   522.4 1425.72   532.2 1426.11   560.1 1429.72   573.7 1430.36
#Mann= 8 ,-1,0
       0     .07       0   166.6    .045       0     175     .07       0
     260     .05       0  308.79     .07       0  318.79     .05       0
  418.79     .06       0  548.79     .05       0
#XS Ineff= 2 , 0
                          246.75         1424.96
Permanent Ineff=
       F       F
Bank Sta=166.6,175
XS Rating Curve= 0 ,0
Exp/Cntr(USF)=0,0
Exp/Cntr=0.3,0.1

Type RM Length L Ch R = 1 ,3272    ,58.7,58.8,61.4
XS GIS Cut Line= 2
2186158.78536603 733014.732342582185776.28720585732868.740678388
#Sta/Elev= 30
       0 1438.61     3.2 1439.13    18.7 1440.34      28 1440.93    32.8 1440.92
    37.3 1439.73    46.6  1434.5    62.7 1430.64    88.4 1427.42   131.2 1423.65
   140.3 1422.23   145.8 1421.48   148.4 1421.51  150.92 1422.21   156.9 1423.36
   161.2 1423.41   186.9 1422.84   206.3 1421.31   212.6 1421.71   221.1 1422.74
     234 1423.22   281.1 1423.54   307.2 1423.19   318.4 1423.49   328.2 1424.61
   349.6 1428.49   366.7 1430.05   374.5 1430.11     397 1428.68   409.4 1428.81
#Mann= 6 ,-1,0
       0     .06       0      10     .05       0     110     .07       0
   140.3    .045       0  150.92     .07       0     220     .05       0
Bank Sta=140.3,150.92
XS Rating Curve= 0 ,0
Exp/Cntr(USF)=0,0
Exp/Cntr=0.3,0.1

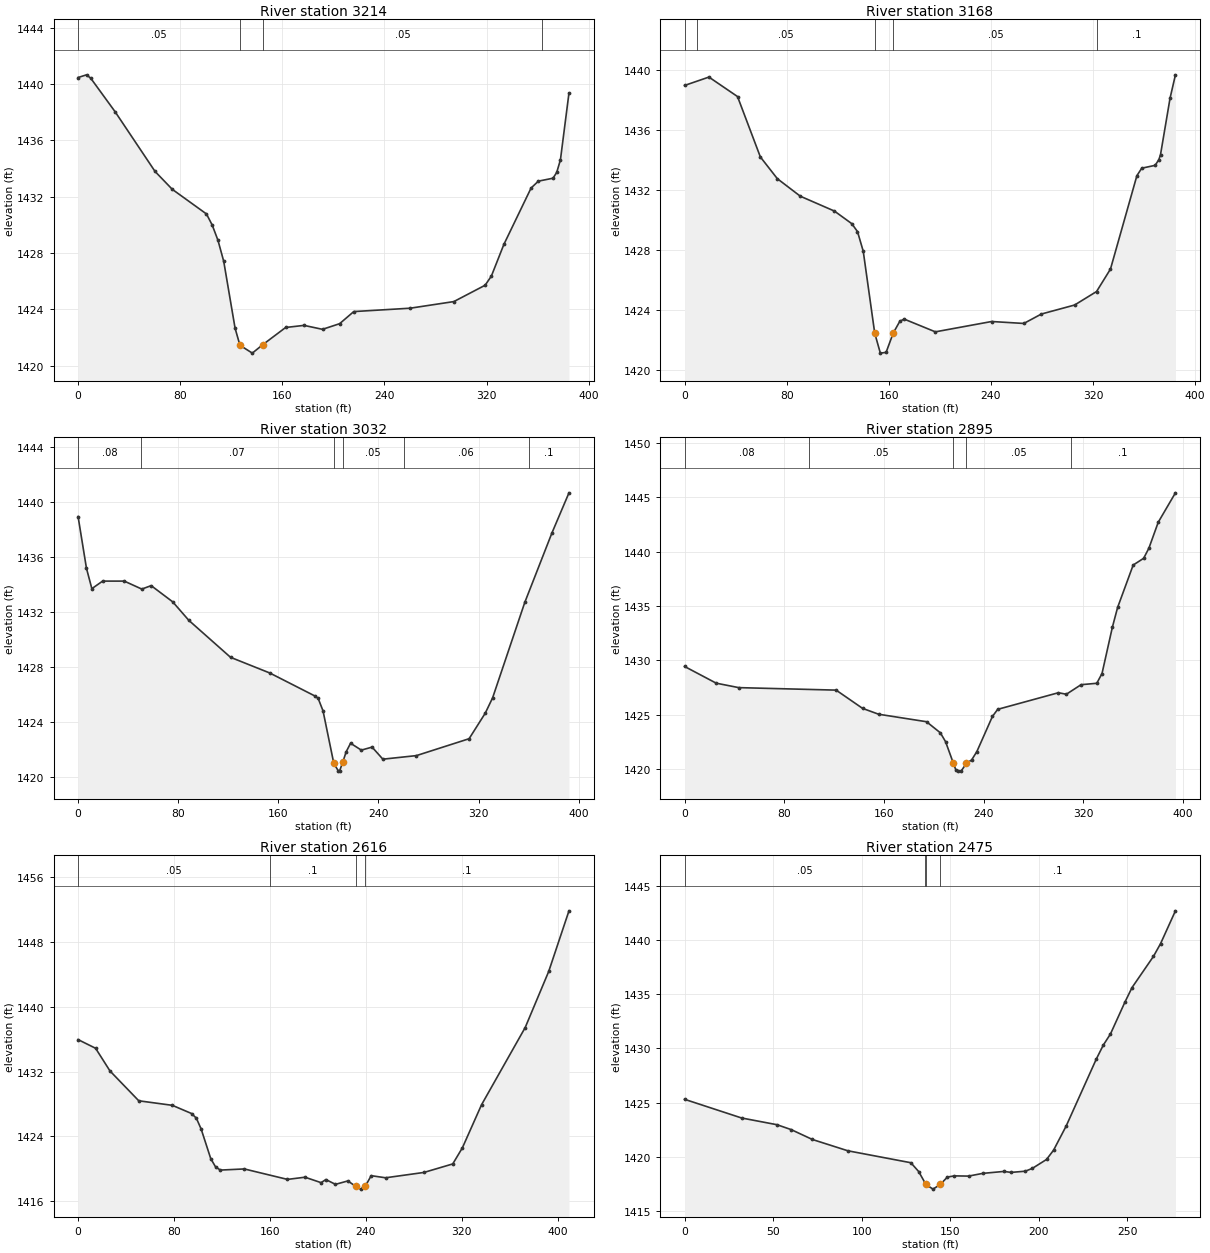
Type RM Length L Ch R = 1 ,3214    ,44.6,45.2,44.4
XS GIS Cut Line= 3
2186158.06235331732965.6438447852186012.07068912732892.107302822
2185884.46316042732711.510207119
#Sta/Elev= 30
       0 1440.47     6.6 1440.66     9.9 1440.42      29 1438.04    60.3  1433.8
    73.8 1432.53   100.6 1430.78   105.1 1429.99   109.6 1428.91   114.1 1427.42
     123 1422.67   126.8 1421.46   136.5  1420.9   144.7  1421.5   162.6 1422.72
     177 1422.87   191.5 1422.59   204.9 1422.99     216 1423.85   260.2 1424.09
   294.4 1424.56   318.9 1425.72   323.8 1426.37   333.6 1428.62   354.9 1432.62
   360.6 1433.11   372.1 1433.32     375 1433.73   377.9 1434.62   384.6 1439.37
#Mann= 4 ,-1,0
       0     .05       0   126.8    .045       0   144.7     .05       0
  363.47      .1       0
Bank Sta=126.8,144.7
XS Rating Curve= 0 ,0
Exp/Cntr(USF)=0,0
Exp/Cntr=0.3,0.1

Type RM Length L Ch R = 1 ,3168    ,137.4,136.8,135.8
XS GIS Cut Line= 3
2186193.20849469 732933.74196261 2186047.2168305732860.205420647
 2185919.6093018732679.608324943
#Sta/Elev= 30
       0 1438.97    19.1 1439.53    41.5 1438.23    59.4  1434.2    72.7 1432.75
    90.7 1431.58   117.4 1430.59     131 1429.75   135.5 1429.22     140 1427.91
     149 1422.44   153.4 1421.11   157.9 1421.16   163.5 1422.45   168.7 1423.24
   172.1 1423.38   196.5 1422.53   240.6 1423.22   265.8 1423.09   279.6 1423.72
   305.6 1424.32   322.8 1425.22   333.7 1426.72   354.4 1432.95   358.2 1433.45
   368.7 1433.64   371.6 1434.02   372.9 1434.35   380.4 1438.13   384.6 1439.68
#Mann= 5 ,-1,0
       0     .06       0      10     .05       0     149    .045       0
   163.5     .05       0  323.47      .1       0
Bank Sta=149,163.5
XS Rating Curve= 0 ,0
Exp/Cntr(USF)=0,0
Exp/Cntr=0.3,0.1

Type RM Length L Ch R = 1 ,3032    ,136.5,136.2,135.9
XS GIS Cut Line= 2
2186294.42938186732813.0555202112185929.99093125732668.145275755
#Sta/Elev= 30
       0 1438.96     6.7 1435.19      11 1433.71    19.6 1434.26    36.9 1434.26
    50.9 1433.68    58.4 1433.93    75.6 1432.75    88.5  1431.4   121.8 1428.71
   153.1 1427.57   189.5 1425.88   191.8 1425.72   195.7 1424.81   204.3 1420.99
     208 1420.42     209 1420.45   211.5 1421.08   214.2 1421.83   217.7 1422.45
   226.3 1421.95   234.9 1422.17   243.5 1421.29   270.3 1421.55   312.4 1422.78
   325.3 1424.64   331.2 1425.76   356.9 1432.71   378.6 1437.77   392.2 1440.69
#Mann= 6 ,-1,0
       0     .08       0      50     .07       0   204.3    .045       0
   211.5     .05       0     260     .06       0     360      .1       0
Bank Sta=204.3,211.5
XS Rating Curve= 0 ,0
Exp/Cntr(USF)=0,0
Exp/Cntr=0.3,0.1

Type RM Length L Ch R = 1 ,2895    ,279.7,279.2,276.8
XS GIS Cut Line= 2
2186352.46764052732671.1652928492185975.80914691732556.318517019
#Sta/Elev= 30
       0 1429.43    25.4 1427.89    43.5 1427.48   121.6 1427.25   142.8 1425.57
   155.7 1425.03   194.1 1424.34   205.2 1423.32   209.4  1422.5  215.691420.506
   217.8 1419.85   219.7 1419.79   221.9  1419.8   226.1  1420.5   230.3 1420.82
   234.5 1421.59     247 1424.83   251.2 1425.48   299.9 1427.01   306.3 1426.87
   318.1 1427.75   330.7 1427.88   334.9 1428.78   343.2 1433.04   347.4 1434.86
   359.9 1438.77   368.3 1439.39   372.5 1440.32     380 1442.71   393.8 1445.42
#Mann= 5 ,-1,0
       0     .08       0     100     .05       0  215.69    .045       0
   226.1     .05       0     310      .1       0
Bank Sta=215.69,226.1
XS Rating Curve= 0 ,0
Exp/Cntr(USF)=0,0
Exp/Cntr=0.3,0.1

Type RM Length L Ch R = 1 ,2616    ,139.8,141.6,141.5
XS GIS Cut Line= 4
2186410.78235899732368.7361017462186185.88694142732367.530903426
 2186168.2338993732375.7284690952186003.32385583 732377.14736243
#Sta/Elev= 30
       0 1435.95    14.6 1434.88    26.6 1432.08    50.6  1428.4    78.6 1427.84
    94.6 1426.83    98.6 1426.26   102.6 1424.92   110.6 1421.27   114.6 1420.25
   118.6 1419.85   138.6 1419.99   174.6  1418.7   189.2 1418.97   202.6  1418.3
   206.6 1418.68   214.6 1418.09   224.9 1418.51   231.71417.826   235.6  1417.5
   239.61417.894   244.4 1419.16   256.4  1418.9   288.4 1419.56   312.4 1420.61
   320.4 1422.59   336.4 1427.91   372.8 1437.44   392.4 1444.36   409.3 1451.84
#Mann= 4 ,-1,0
       0     .05       0     160      .1       0   231.7    .045       0
   239.6      .1       0
Bank Sta=231.7,239.6
XS Rating Curve= 0 ,0
Exp/Cntr(USF)=0,0
Exp/Cntr=0.3,0.1

Type RM Length L Ch R = 1 ,2475    ,57.2,57,57
XS GIS Cut Line= 6
2186292.32136594732236.8814827022186176.72829989732240.363201559
2186155.62248911732241.0916017392186147.12448701732242.791202159
2186075.25566925732242.062801979 2186015.8653647732249.810369409
#Sta/Elev= 30
       0 1425.32    32.2  1423.6    52.2 1422.98    60.2 1422.53    72.2 1421.62
    92.2 1420.58   127.8 1419.48   132.2 1418.67   136.3 1417.48   140.3 1417.05
   144.51417.489   148.4 1418.16   152.4 1418.27   160.4 1418.25   168.4  1418.5
   180.4 1418.68   184.4 1418.59   192.4  1418.7   196.4 1418.96   204.4 1419.78
   208.4 1420.64   215.5 1422.86   232.5 1429.02   236.5 1430.32   240.5 1431.33
   248.6 1434.24   252.7 1435.61   264.8 1438.48   268.8 1439.65   277.2 1442.67
#Mann= 4 ,-1,0
       0     .05       0  135.65      .1       0   136.3    .045       0
   144.5      .1       0
Bank Sta=136.3,144.5
XS Rating Curve= 0 ,0
Exp/Cntr(USF)=0,0
Exp/Cntr=0.3,0.1