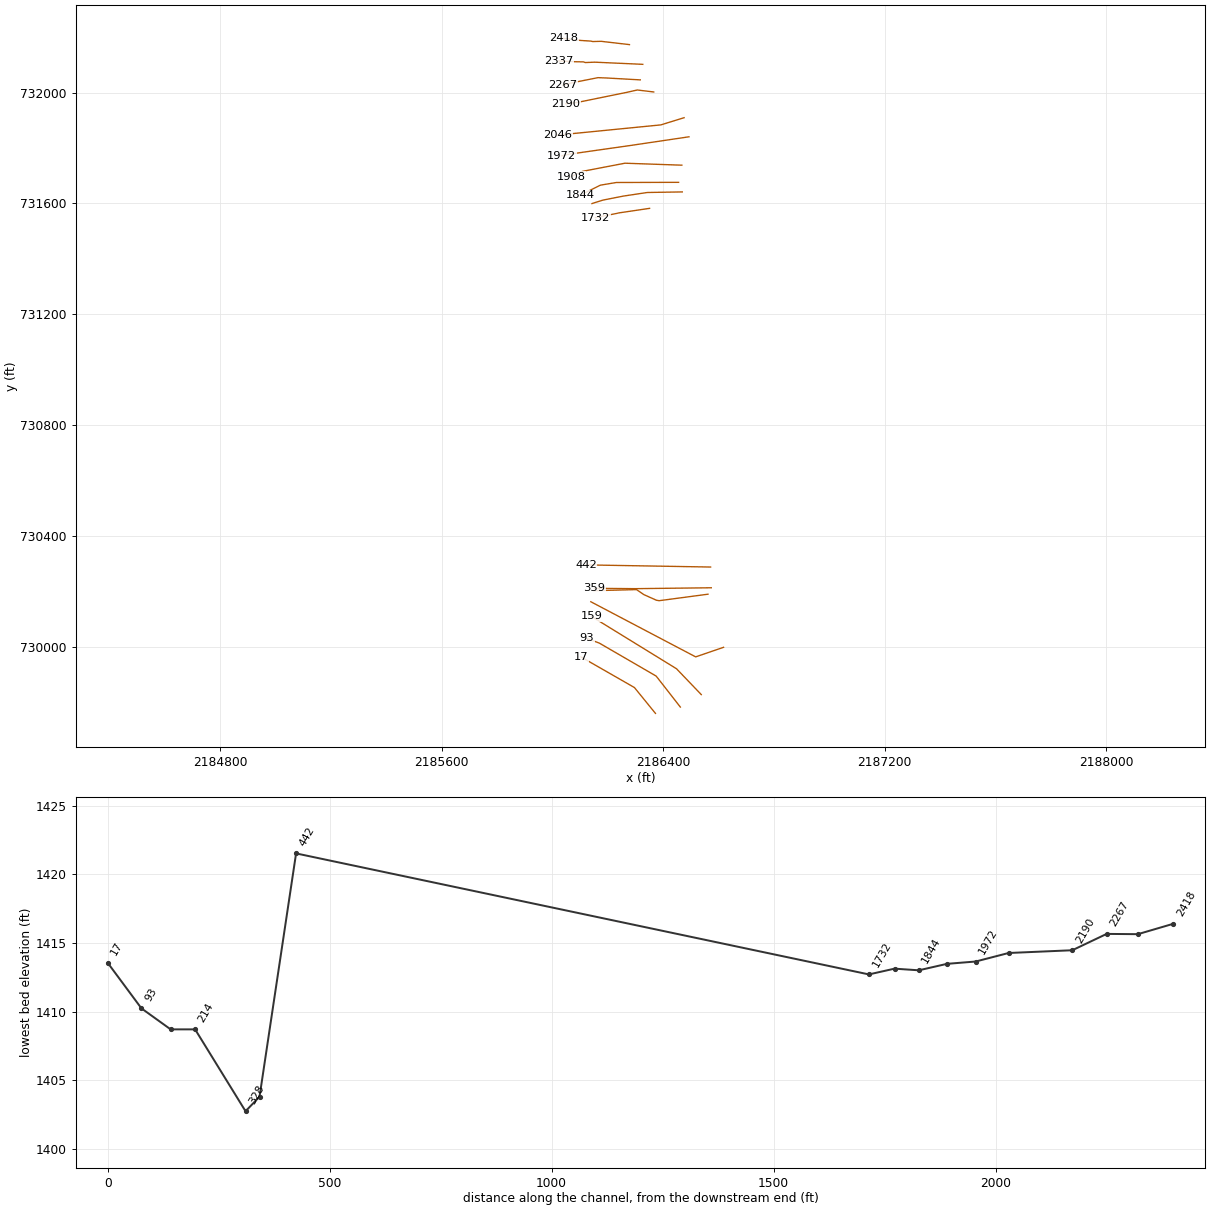
HEC-RAS study FINKRNT1.prj: FINKRNT1

--- FINKRNT1.g01 (geometry) --- (continued)

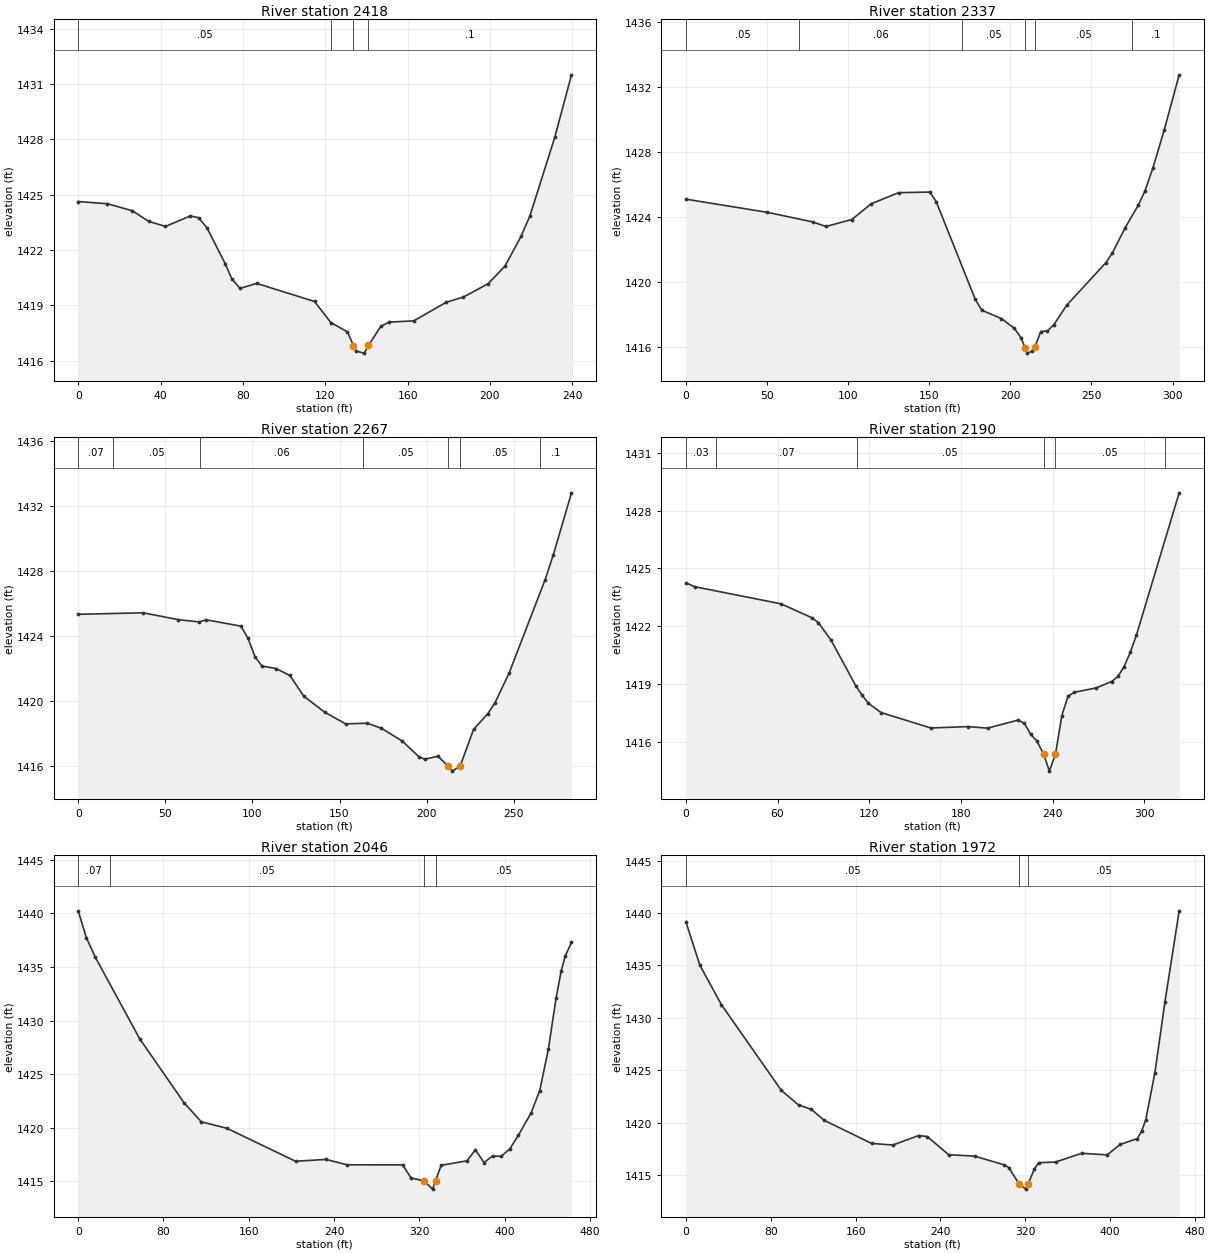
Type RM Length L Ch R = 1 ,2418    ,80.6,80.2,79.7
XS GIS Cut Line= 6
 2186278.2691416732173.7645113282186176.02333857732185.634736482
2186145.80821999732184.8254029492186138.79399604732186.444070016
2186101.02509782732188.8720706152186040.05530498732196.425850259
#Sta/Elev= 30
       0 1424.63    14.2 1424.51    26.3 1424.13    34.3 1423.55    42.4 1423.28
    54.5 1423.85    58.5 1423.75    62.5 1423.21    71.4 1421.26    74.6 1420.44
    78.6 1419.92    86.7 1420.19   114.8 1419.21   122.7 1418.07   130.8 1417.56
   133.71416.818   134.8 1416.53   138.9 1416.41     1411416.827     147 1417.87
     151 1418.09     163 1418.16   178.8 1419.17   187.1 1419.45   199.2 1420.18
   207.3 1421.13   215.1 1422.74   219.4 1423.85   231.5 1428.12   239.6  1431.5
#Mann= 4 ,-1,0
       0     .05       0  122.93      .1       0   133.7    .045       0
     141      .1       0
Bank Sta=133.7,141
XS Rating Curve= 0 ,0
Exp/Cntr(USF)=0,0
Exp/Cntr=0.3,0.1

Type RM Length L Ch R = 1 ,2337    ,68.7,70.2,72
XS GIS Cut Line= 6
2186326.38026716732102.5610519952186152.99666821732110.328801136
2186118.73488196732108.979911914 2186112.2602137732111.407912514
2186081.85977397732111.9474682032186022.97415929732114.993275859
#Sta/Elev= 30
       0 1425.12    50.3 1424.31    78.3 1423.72    86.3 1423.44   102.3 1423.87
   114.3 1424.84   131.1 1425.52   150.4 1425.56   154.4 1424.95   178.4 1418.96
   182.4 1418.29   194.4 1417.78   202.4 1417.19   206.6  1416.6   209.11415.979
   210.6 1415.65   213.1 1415.76   215.11416.007   218.8 1416.98   222.8 1417.01
   226.8 1417.39   234.8  1418.6   258.9 1421.21   262.9 1421.81   270.8 1423.36
   278.9 1424.75   282.9  1425.6   287.9 1427.04   294.9 1429.38   304.1 1432.77
#Mann= 6 ,-1,0
       0     .05       0      70     .06       0     170     .05       0
   209.1    .045       0   215.1     .05       0  275.17      .1       0
Bank Sta=209.1,215.1
XS Rating Curve= 0 ,0
Exp/Cntr(USF)=0,0
Exp/Cntr=0.3,0.1

Type RM Length L Ch R = 1 ,2267    ,77.2,77.4,76.9
XS GIS Cut Line= 5
2186317.47526849 732046.404383932186194.80140092732053.270873998
2186164.53459802732054.4427984292186064.45241329732034.557473517
2186037.61827343732026.791799821
#Sta/Elev= 30
       0 1425.33    37.4 1425.42    57.4    1425    69.4 1424.86    73.4 1424.99
    93.4  1424.6    97.5 1423.84   101.5 1422.71   105.5 1422.14   113.5 1421.99
   121.5 1421.56   129.5 1420.28   141.5  1419.3   153.5 1418.58   165.8 1418.62
   173.9 1418.32   186.1 1417.51   195.4 1416.57   198.8  1416.4   206.5 1416.59
   212.4 1415.96   214.7 1415.67   219.2 1415.98   226.9 1418.24   235.1 1419.21
   239.2 1419.88   247.3 1421.71     268 1427.47   272.7    1429   283.1 1432.81
#Mann= 7 ,-1,0
       0     .07       0      20     .05       0      70     .06       0
  163.16     .05       0   212.4    .045       0   219.2     .05       0
  265.19      .1       0
Bank Sta=212.4,219.2
XS Rating Curve= 0 ,0
Exp/Cntr(USF)=0,0
Exp/Cntr=0.3,0.1

Type RM Length L Ch R = 1 ,2190    ,142.6,143.5,142.2
XS GIS Cut Line= 5
2186365.88053906732002.769114211 2186306.5942268732009.885656005
2186265.55163487732000.713194044  2186087.325478731964.383040792
2186048.28663955731959.935360046
#Sta/Elev= 30
       0 1424.25     5.7 1424.05    62.3 1423.16    82.7 1422.43    86.8 1422.18
      95 1421.28   111.3  1418.9   115.4 1418.41   119.5    1418   127.7 1417.52
   160.3 1416.72   184.8 1416.79   197.5 1416.71   217.5 1417.13   221.6 1416.96
   225.6  1416.4   229.7 1416.05   234.31415.348   237.9 1414.48   241.9 1415.35
   246.1 1417.36   250.1 1418.36   254.2 1418.57   268.7  1418.8   278.7 1419.13
   282.8 1419.39   286.8  1419.9   290.9 1420.64   294.9 1421.53   322.9 1428.92
#Mann= 6 ,-1,0
       0     .03       0      20     .07       0  111.77     .05       0
   234.3    .045       0   241.9     .05       0  313.66      .1       0
Bank Sta=234.3,241.9
XS Rating Curve= 0 ,0
Exp/Cntr(USF)=0,0
Exp/Cntr=0.3,0.1

Type RM Length L Ch R = 1 ,2046    ,71.7,74.1,73.2
XS GIS Cut Line= 4
2186475.56025025731909.8459573912186391.89998321731883.882426239
 2186029.5644818731848.1104499862186018.60210198731846.379547909
#Sta/Elev= 30
       0 1440.24     7.7 1437.72      16 1435.92    57.6 1428.32    99.4 1422.32
   115.5 1420.56   139.6 1419.95   203.9 1416.88   232.5 1417.05   252.1 1416.55
   304.4 1416.54   312.4 1415.31   324.5 1415.06   332.5 1414.28  335.25 1415.06
   340.5  1416.5   364.7 1416.92   372.7 1417.95   380.7 1416.76   388.8 1417.37
   396.8 1417.34   404.9 1418.03   412.9 1419.29     425  1421.4     433 1423.48
   441.1 1427.33   448.3 1432.07   453.1 1434.63   457.1 1436.07   462.8 1437.29
#Mann= 4 ,-1,0
       0     .07       0      30     .05       0   324.5    .045       0
  335.25     .05       0
Bank Sta=324.5,335.25
XS Rating Curve= 0 ,0
Exp/Cntr(USF)=0,0
Exp/Cntr=0.3,0.1

Type RM Length L Ch R = 1 ,1972    ,64.5,64.6,64.9
XS GIS Cut Line= 4
2186493.23663488731840.8371768472186282.51623295731809.603472683
2186062.54123557 731778.268002972186033.42345907731772.131213187
#Sta/Elev= 30
       0 1439.17    13.2 1435.02    33.4 1431.27      90 1423.08   106.2 1421.69
   118.3 1421.27   130.5 1420.22     175 1418.02   195.2 1417.87   219.4 1418.77
   227.5 1418.68   247.7 1416.94   272.1 1416.81   300.2 1415.97   304.3 1415.72
     314 1414.18   320.4 1413.66   322.81414.194   328.5 1415.58   332.6 1416.18
   348.7 1416.25     373 1417.08   397.2 1416.93   409.3 1417.92   425.5 1418.48
   429.5 1419.16   433.6  1420.3   442.1 1424.76   451.6 1431.52     465 1440.21
#Mann= 3 ,-1,0
       0     .05       0     314    .045       0   322.8     .05       0
Bank Sta=314,322.8
XS Rating Curve= 0 ,0
Exp/Cntr(USF)=0,0
Exp/Cntr=0.3,0.1

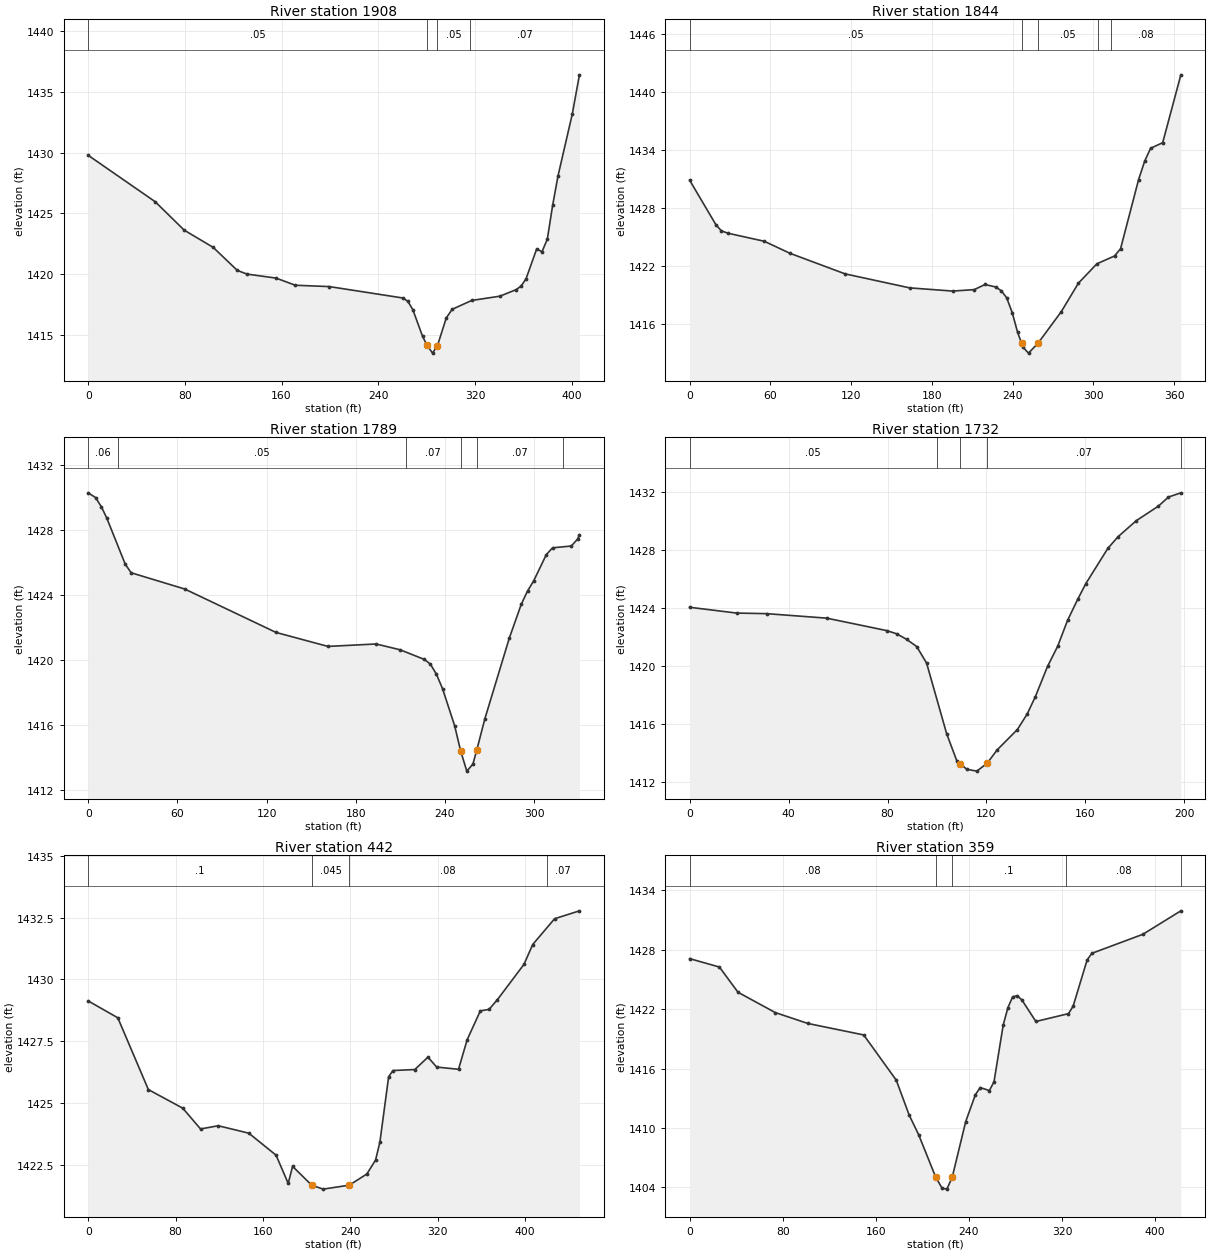
Type RM Length L Ch R = 1 ,1908    ,63.7,63.5,63.1
XS GIS Cut Line= 4
2186467.50224769731738.3482503142186261.94938307731745.458300222
2186108.20059291731715.9976042742186068.06097079731697.349456487
#Sta/Elev= 30
       0 1429.78    55.4 1425.96    79.4 1423.62   103.4  1422.2   123.4  1420.3
   131.4    1420   155.4 1419.67   171.4 1419.08   199.5 1418.97   260.4 1418.03
   264.5 1417.76   268.6 1417.07   276.7 1414.87   280.2 1414.17   284.9 1413.49
     2891414.107   296.3 1416.39   301.2  1417.1   317.4 1417.83   340.7 1418.18
   354.1 1418.72   358.2 1419.01   362.3 1419.61   371.1 1422.07   375.5 1421.84
   379.9 1422.87   384.3 1425.65   388.7 1428.06   400.5 1433.15   406.5 1436.41
#Mann= 4 ,-1,0
       0     .05       0   280.2    .045       0     289     .05       0
  315.68     .07       0
Bank Sta=280.2,289
XS Rating Curve= 0 ,0
Exp/Cntr(USF)=0,0
Exp/Cntr=0.3,0.1

Type RM Length L Ch R = 1 ,1844    ,54.2,54.7,54.6
XS GIS Cut Line= 4
2186455.64756971 731676.413292952186230.90018801731675.821601936
2186173.36826562731666.2329482042186100.11657869731629.638720243
#Sta/Elev= 30
       0 1430.91    19.5 1426.31    23.5 1425.68    28.3 1425.43    55.5 1424.59
    74.5 1423.35   115.5 1421.22   163.5 1419.77   195.5 1419.44   211.5 1419.59
   219.5 1420.12   227.5 1419.86   231.6 1419.47   235.6 1418.74   239.7 1417.21
   243.7 1415.17   246.61414.067   247.8 1413.61   251.8 1413.02   258.9 1414.05
   276.2 1417.32   288.9 1420.26   302.6 1422.26   315.7 1423.07   320.2 1423.82
   333.6 1430.97   338.1 1432.87   342.5 1434.21   351.5 1434.79     365 1441.81
#Mann= 5 ,-1,0
       0     .05       0   246.6    .045       0   258.9     .05       0
  303.07     .07       0  313.07     .08       0
Bank Sta=246.6,258.9
XS Rating Curve= 0 ,0
Exp/Cntr(USF)=0,0
Exp/Cntr=0.3,0.1

Type RM Length L Ch R = 1 ,1789    ,58.2,57.7,58.4
XS GIS Cut Line= 5
2186469.09394658731641.7896016292186342.57980207731639.723140828
2186256.28191848731626.7502563662186181.82884244731612.085256541
2186142.91018906731599.676410535
#Sta/Elev= 30
       0  1430.3     4.9 1430.01     8.9 1429.43    12.5 1428.74    24.9  1425.9
    28.9 1425.37    64.9 1424.37   126.4 1421.69   161.3 1420.83   193.7 1420.98
   209.9 1420.62   226.1 1420.03   230.2 1419.74   234.3 1419.11   238.4 1418.22
   246.5 1415.95   250.51414.408   254.7 1413.14   258.8 1413.57   261.41414.434
   266.9 1416.38   283.3 1421.34   291.4 1423.44   295.6 1424.25   299.7 1424.87
   308.2 1426.49   312.4 1426.91     325 1427.02   329.2 1427.44   330.5 1427.71
#Mann= 6 ,-1,0
       0     .06       0      20     .05       0   213.8     .07       0
   250.5    .045       0   261.4     .07       0  319.68     .08       0
Bank Sta=250.5,261.4
XS Rating Curve= 0 ,0
Exp/Cntr(USF)=0,0
Exp/Cntr=0.3,0.1

Type RM Length L Ch R = 1 ,1732    ,1291.9,1290.1,1280.5
XS GIS Cut Line= 4
2186350.96688206731582.429626911 2186239.0447647 731565.85974852
2186230.83646787 731563.823103442186155.30303162731549.008132983
#Sta/Elev= 30
       0 1424.03      19 1423.63    31.1 1423.59    55.4 1423.28    79.7 1422.42
    83.7  1422.2    87.7 1421.82    91.8 1421.32    95.8 1420.18   103.9 1415.31
     108 1413.44   109.51413.223     112 1412.85   116.1 1412.72   120.31413.263
   124.3 1414.18   132.5 1415.59   136.5 1416.67   139.8 1417.87   144.7 1419.95
   148.8 1421.34   152.8 1423.13   156.9 1424.58   160.2 1425.67   169.1  1428.1
   173.2  1428.9   180.6 1430.01   189.5 1431.01   193.6 1431.64   198.6 1431.93
#Mann= 5 ,-1,0
       0     .05       0     100     .07       0   109.5    .045       0
   120.3     .07       0  198.57     .08       0
Bank Sta=109.5,120.3
XS Rating Curve= 0 ,0
Exp/Cntr(USF)=0,0
Exp/Cntr=0.3,0.1

Type RM Length L Ch R = 1 ,442     ,81.4,82.3,83.5
XS GIS Cut Line= 2
 2186571.3001018730287.1646548132186121.33412673 730294.89684185
#Sta/Elev= 30
       0 1429.13    27.1 1428.45    55.1 1425.55    86.6  1424.8   102.9 1423.96
   119.1 1424.09   147.1 1423.79   172.1  1422.9   183.2 1421.76   187.2 1422.45
   204.7 1421.69   215.2 1421.53   239.2 1421.69   255.2 1422.14   263.2  1422.7
   267.2 1423.43   275.2 1426.07   279.2 1426.32   299.2 1426.36   311.2 1426.86
   319.2 1426.46   339.2 1426.37   347.2 1427.57   359.2 1428.73   367.2 1428.79
   374.8 1429.18   399.2 1430.61   407.2 1431.41   427.2 1432.45     450 1432.77
#Mann= 4 ,-1,0
       0      .1       0   204.7    .045       0   239.2     .08       0
     420     .07       0
Bank Sta=204.7,239.2
XS Rating Curve= 0 ,0
Exp/Cntr(USF)=0,0
Exp/Cntr=0.3,0.1

Type RM Length L Ch R = 1 ,359     ,38.9,31.5,27.9
XS GIS Cut Line= 3
2186573.75178776730212.2933325762186300.17790372730209.070915908
2186151.62406618730210.233202737
#Sta/Elev= 30
       0 1427.11    25.6 1426.26    41.6 1423.71    73.6 1421.66   101.6 1420.56
   149.6  1419.4   177.6 1414.83   188.7  1411.3   196.8 1409.33   211.51405.027
     217 1403.91   221.1 1403.82   225.7 1405.03   237.3 1410.65   245.6 1413.36
   249.8 1414.08   257.6 1413.78   261.6 1414.66   269.5 1420.39   273.6 1422.17
   277.6 1423.24   281.6 1423.37   285.6 1422.93   297.6 1420.76   325.6 1421.55
   329.6  1422.3   341.6 1426.96   345.6 1427.64   389.6 1429.57   422.2 1431.94
#Mann= 5 ,-1,0
       0     .08       0   211.5    .045       0   225.7      .1       0
  323.59     .08       0  422.15     .07       0
Bank Sta=211.5,225.7
XS Rating Curve= 0 ,0
Exp/Cntr(USF)=0,0
Exp/Cntr=0.3,0.1

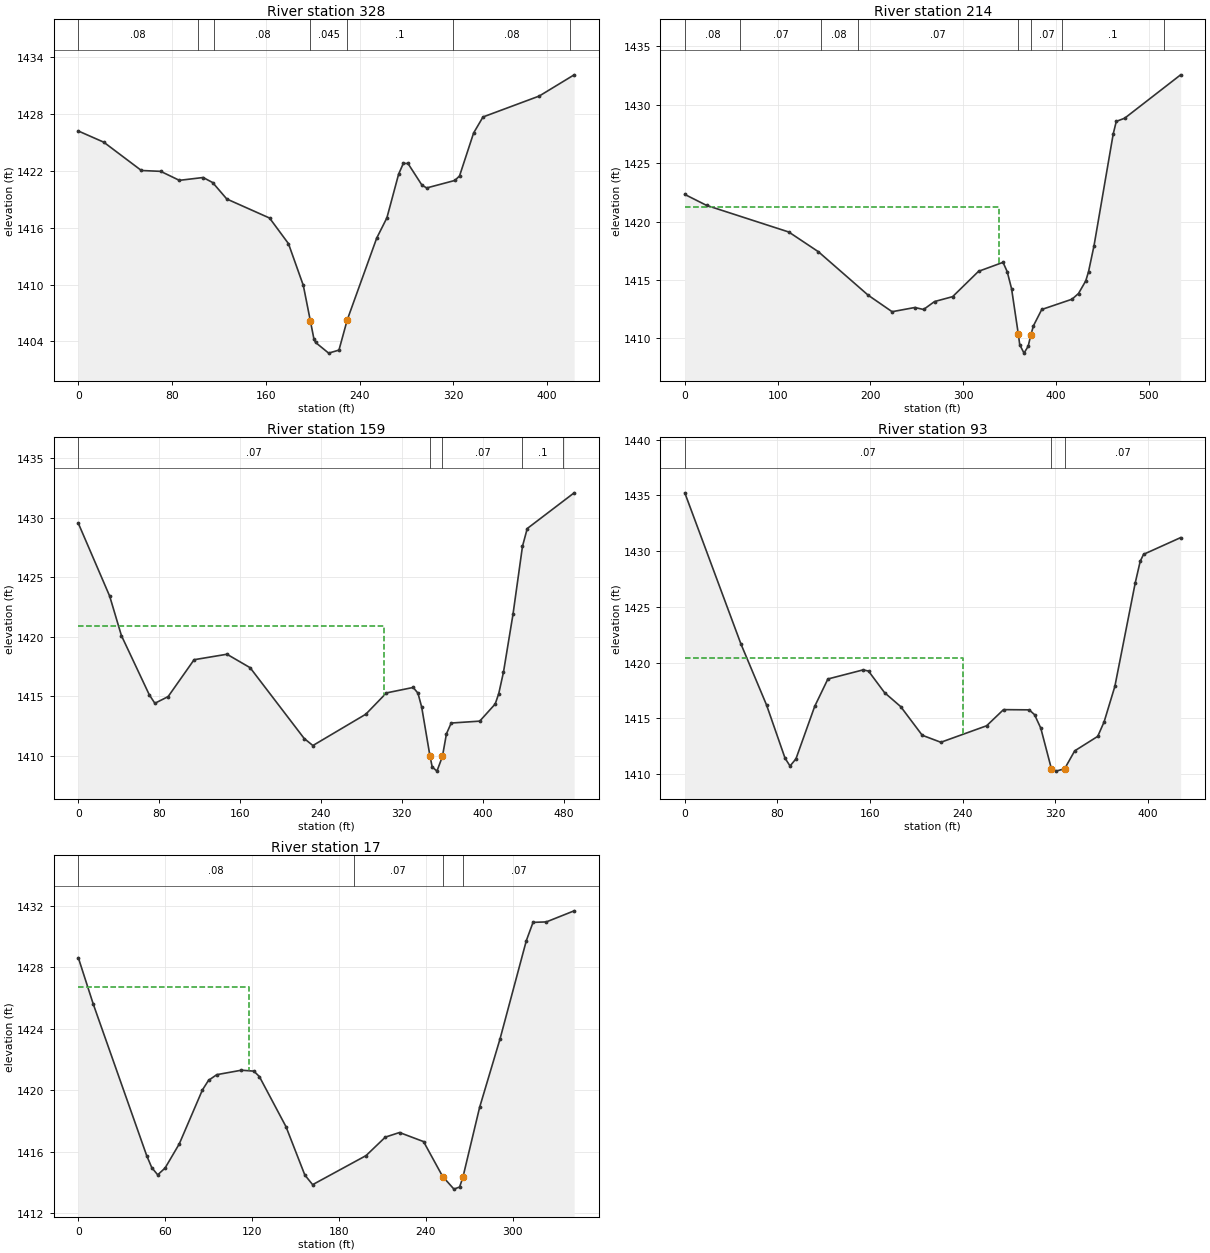
Type RM Length L Ch R = 1 ,328     ,116.6,113.6,112.5
XS GIS Cut Line= 6
2186561.77122782730189.0574158112186385.78324905730165.663243406
2186375.68122005730167.2583006162186330.48793246730187.462358601
2186303.69892703730205.6679761482186150.38345131730201.766539228
#Sta/Elev= 30
       0 1426.21    21.7 1425.03    53.8 1422.04    70.3 1421.95    86.2    1421
   106.5  1421.3   114.6 1420.77   126.7 1419.03   163.2 1417.02   179.3 1414.32
     192  1409.9     198 1406.16     201 1404.28   202.4 1403.89   213.6 1402.76
   222.4 1403.08   229.51406.281   254.6  1414.9   263.3 1417.04   273.3 1421.65
   277.3 1422.79   281.3 1422.78   293.3 1420.48   297.3  1420.2   321.3 1420.99
   325.3 1421.47   337.3    1426   345.3 1427.69   393.3  1429.9   423.1 1432.14
#Mann= 7 ,-1,0
       0     .08       0   101.8     .07       0  116.16     .08       0
     198    .045       0   229.5      .1       0  319.75     .08       0
  419.75     .07       0
Bank Sta=198,229.5
XS Rating Curve= 0 ,0
Exp/Cntr(USF)=0,0
Exp/Cntr=0.3,0.1

Type RM Length L Ch R = 1 ,214     ,55.8,55.1,54.8
XS GIS Cut Line= 3
2186618.01132196729997.2432604332186517.41641158729962.732802998
2186138.80515916730161.811369806
#Sta/Elev= 30
       0 1422.32    23.5 1421.38     112  1419.1   143.9 1417.41   197.6 1413.68
   223.3 1412.27   247.8 1412.63   257.2 1412.46     269 1413.14   288.5 1413.56
   316.4 1415.73   342.8  1416.5   347.3  1415.7     352 1414.24   359.31410.329
   360.8 1409.44   365.4 1408.72   369.9 1409.31   372.7 1410.27   375.6 1411.07
   384.5 1412.46   417.1 1413.34   424.1 1413.83   431.9 1414.91   434.9  1415.7
   440.8 1417.92   461.5 1427.51   464.8 1428.58   473.8 1428.85   534.1 1432.57
#Mann= 8 ,-1,0
       0     .08       0      60     .07       0  146.35     .08       0
  186.35     .07       0   359.3    .045       0   372.7     .07       0
  406.35      .1       0  516.35     .07       0
#XS Ineff= 2 , 0
          338.16 1421.23
Permanent Ineff=
       F       F
Bank Sta=359.3,372.7
XS Rating Curve= 0 ,0
Exp/Cntr(USF)=0,0
Exp/Cntr=0.3,0.1

Type RM Length L Ch R = 1 ,159     ,65.8,65.8,66
XS GIS Cut Line= 3
2186537.63030153729826.5285105492186448.19399427729919.856935194
2186140.61250271 730109.15046649
#Sta/Elev= 30
       0 1429.54      31 1423.42    42.6 1420.11    70.2 1415.13    75.7 1414.42
    88.8 1414.98   114.5 1418.08     147 1418.54   169.9 1417.41   223.4 1411.46
     232 1410.87   284.3  1413.5   304.7 1415.29   331.2 1415.75   335.9 1415.27
   339.6  1414.1   347.71410.028     350 1409.07   354.7 1408.72   360.1 1409.95
   364.1 1411.86   368.8 1412.76     397 1412.92   412.3 1414.36   415.8 1415.23
   420.5 1417.04   429.9 1421.89   439.3 1427.61     444  1429.1   490.4  1432.1
#Mann= 5 ,-1,0
       0     .07       0   347.7    .045       0   360.1     .07       0
  439.26      .1       0  479.26     .07       0
#XS Ineff= 2 , 0
          301.94 1420.89
Permanent Ineff=
       F       F
Bank Sta=347.7,360.1
XS Rating Curve= 0 ,0
Exp/Cntr(USF)=0,0
Exp/Cntr=0.3,0.1

Type RM Length L Ch R = 1 ,93      ,76,76.1,76.2
XS GIS Cut Line= 4
2186462.01082639729781.4932388112186374.75472013729893.385194504
2186169.75921805730012.3074873672186123.59343141730029.847398039
#Sta/Elev= 30
       0 1435.23    48.5 1421.66    70.6 1416.19    86.6 1411.41    90.9 1410.71
      96 1411.35   112.2 1416.06   123.6 1418.52   154.1 1419.34   158.7 1419.23
   172.6 1417.29   186.5 1416.04   205.1 1413.47   221.2 1412.84   260.7 1414.32
   275.3 1415.77   297.5 1415.75   302.1 1415.32   307.5 1414.11   316.7 1410.45
   320.6 1410.25   328.11410.461   336.8 1412.07   356.7 1413.37   362.2 1414.67
   371.5 1417.86   389.1 1427.15   393.4 1429.09   396.3 1429.71   428.3 1431.21
#Mann= 3 ,-1,0
       0     .07       0   316.7    .045       0   328.1     .07       0
#XS Ineff= 2 , 0
          239.96 1420.38
Permanent Ineff=
       F       F
Bank Sta=316.7,328.1
XS Rating Curve= 0 ,0
Exp/Cntr(USF)=0,0
Exp/Cntr=0.3,0.1

Type RM Length L Ch R = 1 ,17      ,,,
XS GIS Cut Line= 3
2186372.14499826 729758.691556742186296.23080243729851.997969477
2186103.52127596729962.426795371
#Sta/Elev= 30
       0 1428.61    10.3  1425.6    47.2 1415.75    50.7 1414.97    54.8  1414.5
    59.9 1414.94    69.7 1416.51    85.7 1420.02    89.9 1420.64    95.6 1421.01
   112.6  1421.3   121.2 1421.24     125 1420.89   143.4 1417.63   156.4 1414.49
   161.8 1413.86   198.7 1415.75     212 1416.95   221.8 1417.25   238.4 1416.66
   251.6 1414.39   259.4 1413.57   263.3 1413.71   265.61414.352   277.1 1418.88
   291.2 1423.33   309.4 1429.73     314 1430.91   323.2 1430.94   342.4 1431.66
#Mann= 4 ,-1,0
       0     .08       0  190.29     .07       0   251.6    .045       0
   265.6     .07       0
#XS Ineff= 2 , 0
          117.76 1426.68
Permanent Ineff=
       F       F
Bank Sta=251.6,265.6
XS Rating Curve= 0 ,0
Exp/Cntr(USF)=0,0
Exp/Cntr=0.3,0.1
LCMann Table=0

Chan Stop Cuts=-1
Use User Specified Reach Order=0
Composite Channel Slope=5